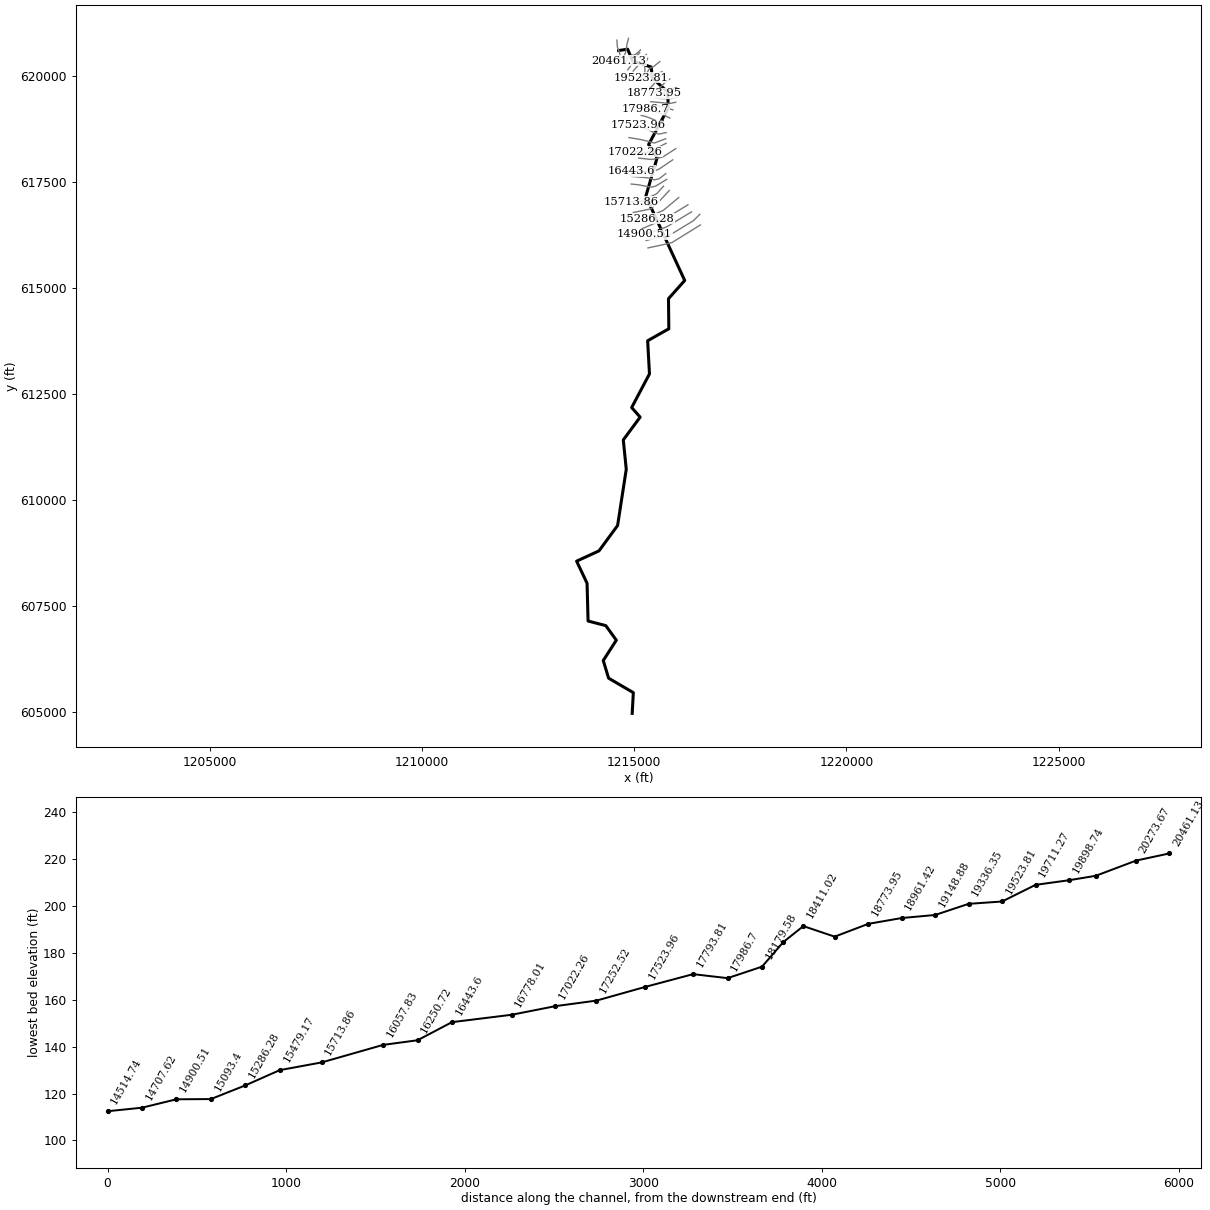
--- 76_ras.prj (project) ---

Proj Title=76
Current Plan=p01
Default Exp/Contr=0.3,0.1
English Units
Geom File=g01
Flow File=f01
Plan File=p01
Y Axis Title=Elevation
X Axis Title(PF)=Main Channel Distance
X Axis Title(XS)=Station
BEGIN DESCRIPTION:
RFD model 76 exported to HEC-RAS
END DESCRIPTION:

--- 76_ras.p01 (plan) ---

Plan Title=Plan 01
Program Version=4.10
Short Identifier=Plan 01
Geom File=g01
Flow File=f01
Subcritical Flow
Calc Critical at every XS
Secant Critical Depth

--- 76_ras.f01 (steady flow) ---

Flow Title=Flow 01
Program Version=5.01
Number of Profiles= 5
Profile Names=10yr,25yr,50yr,100yr,500yr
River Rch & RM=76,80,20461.13
  971.53  971.53  971.53 1997.07 2792.96
River Rch & RM=76,80,20273.67
  974.93  974.93  974.93 2006.35 2807.79
River Rch & RM=76,80,20049.15
  977.04  977.04  977.04 2012.13 2817.04
River Rch & RM=76,80,19898.74
  986.47  986.47  986.47 2037.95 2858.39
River Rch & RM=76,80,19711.27
  989.59  989.59  989.59 2046.49 2872.09
River Rch & RM=76,80,19523.81
 1001.08 1001.08 1001.08 2078.09 2922.83
River Rch & RM=76,80,19336.35
 1004.53 1004.53 1004.53  2087.6 2938.12
River Rch & RM=76,80,19148.88
 1005.54 1005.54 1005.54 2090.39 2942.61
River Rch & RM=76,80,18961.42
 1006.55 1006.55 1006.55 2093.17 2947.09
River Rch & RM=76,80,18773.95
 1012.37 1012.37 1012.37 2109.26    2973
River Rch & RM=76,80,18586.49
 1016.36 1016.36 1016.36  2120.3 2990.78
River Rch & RM=76,80,18411.02
 1018.14 1018.14 1018.14 2125.24 2998.75
River Rch & RM=76,80,18298.93
 1020.52 1020.52 1020.52 2131.82 3009.37
River Rch & RM=76,80,18179.58
 1021.51 1021.51 1021.51 2134.56 3013.78
River Rch & RM=76,80, 17986.7
 1022.88 1022.88 1022.88 2138.38 3019.96
River Rch & RM=76,80,17793.81
 1027.79 1027.79 1027.79    2152 3041.94
River Rch & RM=76,80,17523.96
 1032.65 1032.65 1032.65 2165.53 3063.81
River Rch & RM=76,80,17252.52
 1038.06 1038.06 1038.06  2180.6 3088.19
River Rch & RM=76,80,17022.26
 1040.94 1040.94 1040.94 2188.63  3101.2
River Rch & RM=76,80,16778.01
 1044.95 1044.95 1044.95 2199.83 3119.35
River Rch & RM=76,80, 16443.6
 1048.18 1048.18 1048.18 2208.86 3133.99
River Rch & RM=76,80,16250.72
 1067.81 1067.81 1067.81 2263.91 3223.41
River Rch & RM=76,80,16057.83
 1068.91 1068.91 1068.91 2267.02 3228.47
River Rch & RM=76,80,15713.86
 1130.04 1130.04 1130.04 2440.68 3512.65
River Rch & RM=76,80,15479.17
 1134.58 1134.58 1134.58 2453.73 3534.11
River Rch & RM=76,80,15286.28
  1137.6  1137.6  1137.6 2462.39 3548.37
River Rch & RM=76,80, 15093.4
 1139.94 1139.94 1139.94  2469.1 3559.44
River Rch & RM=76,80,14900.51
 1143.26 1143.26 1143.26 2478.67 3575.21
River Rch & RM=76,80,14707.62
 1147.57 1147.57 1147.57 2491.06 3595.63
River Rch & RM=76,80,14514.74
 1148.23 1148.23 1148.23 2492.96 3598.77
River Rch & RM=76,80,14321.85
  1152.5  1152.5  1152.5 2505.28 3619.11
River Rch & RM=76,80,14128.96
 1161.46 1161.46 1161.46 2531.17 3661.88
River Rch & RM=76,80,13936.08
 1164.37 1164.37 1164.37 2539.59 3675.81
River Rch & RM=76,80, 13550.3
 1199.07 1199.07 1199.07 2640.53 3843.26
River Rch & RM=76,80,13357.42
 1199.69 1199.69 1199.69 2642.33 3846.26
River Rch & RM=76,80,13191.21
 1209.19 1209.19 1209.19 2670.14 3892.55
River Rch & RM=76,80,12898.19
 1211.92 1211.92 1211.92 2678.16 3905.92
River Rch & RM=76,80,   12712
 1214.04 1214.04 1214.04 2684.38  3916.3
River Rch & RM=76,80,12525.81
  1214.2  1214.2  1214.2 2684.83 3917.04
River Rch & RM=76,80,12339.62
    1931    1931    1931    4969    7916
Boundary for River Rch & Prof#=76,80,1
Up Type= 0
Dn Type= 2
Boundary for River Rch & Prof#=76,80,2
Up Type= 0
Dn Type= 2
Boundary for River Rch & Prof#=76,80,2
Up Type= 0
Dn Type= 2
Boundary for River Rch & Prof#=76,80,2
Up Type= 0
Dn Type= 2
Boundary for River Rch & Prof#=76,80,2
Up Type= 0
Dn Type= 2

--- 76_ras.g01 (geometry) ---

Geom Title=76
Program Version=4.10

River Reach=76,80
Reach XY= 30
1214634.06277419620590.2495536861214845.72937932620621.916204827
1214960.72933756620351.9162816371215400.72920333 620201.08298036
 1215427.3958547619944.4163891361215789.89573812619612.749810445
1215801.56239042619236.0832552991215339.89583515618377.750190118
1215539.06243391618061.9169448221215274.06248599617160.250553508
1216189.89549153615174.417783281 1215808.2289251614746.084588178
1215815.72890235614036.9181318561215317.39570794613755.251563253
1215359.89567278612973.585127452 1214940.7291069612181.918707972
1215139.89570824611956.0854359541214743.22914311  611419.4189401
1214813.22910242610727.7524767971214609.06245766609402.752876166
1214170.72923644 608806.086399361213644.06271815608563.586486591
1213889.89596388608043.5866339131213914.06259764 607153.58689751
1214330.72913827607046.0869173851214579.06238837 606702.75367883
1214271.56246521606223.587163337 1214397.3957494605807.753949857
1214979.89556761605466.9207009381214953.22889467604978.587513388

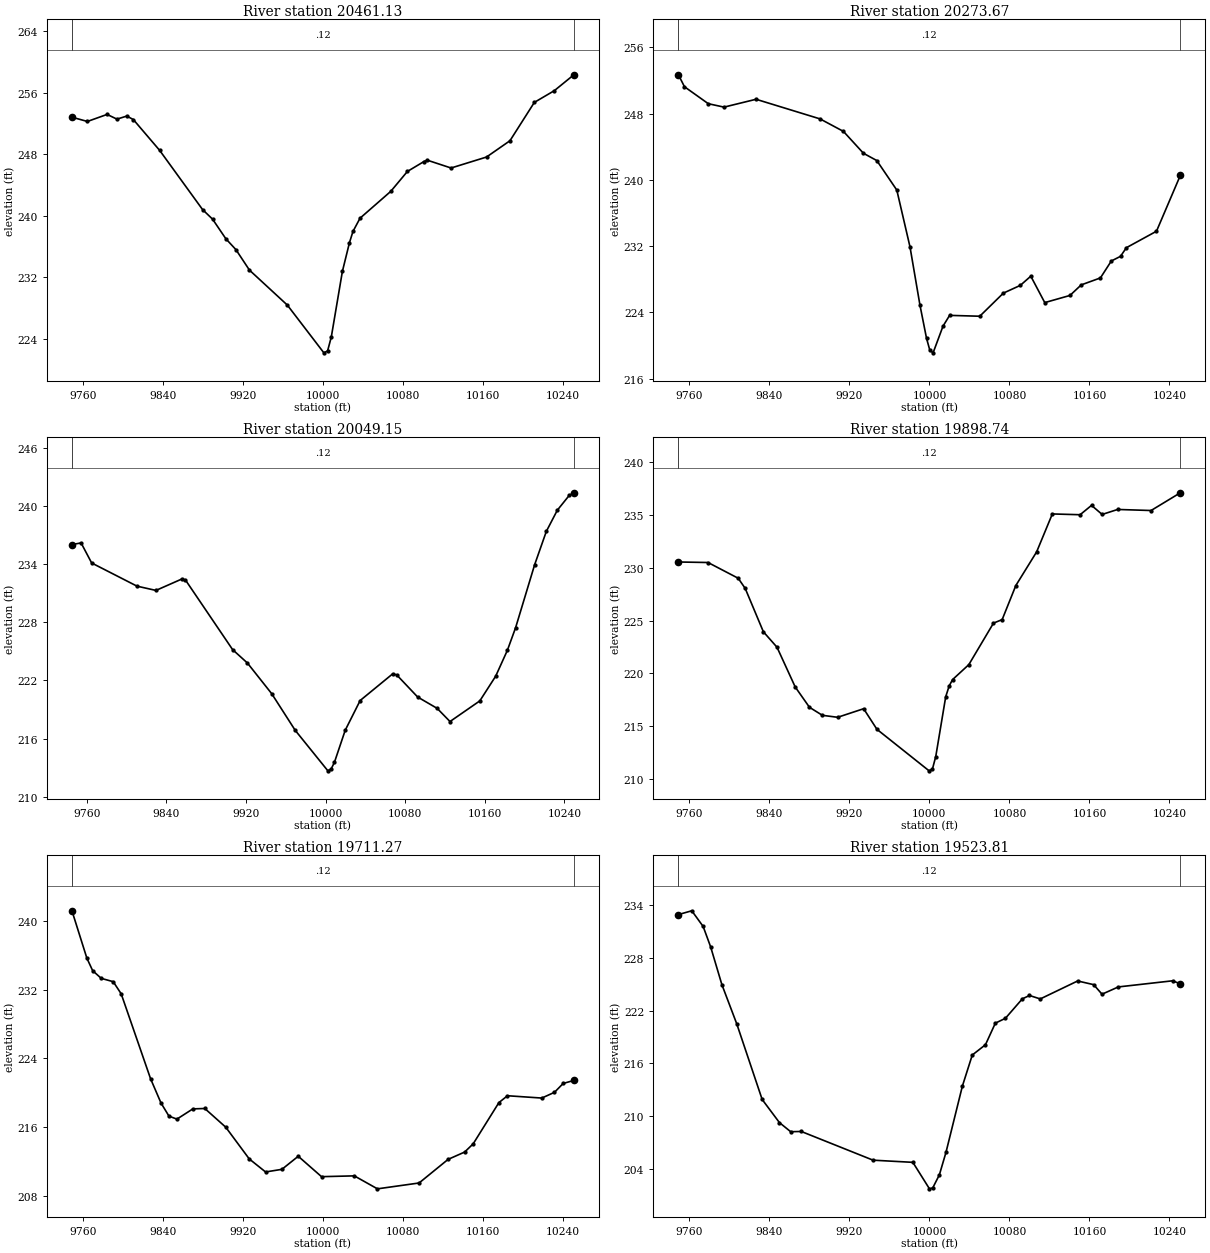
Type RM Length L Ch R = 1 ,20461.13,187.464700,187.464700,187.464700
XS GIS Cut Line= 6
1214592.77230845620835.0556364481214603.09579016620679.688161506
1214652.07555993620553.0369048631214663.46853031 620499.30297693
1214660.48078969620425.8675522881214638.32044803620348.371447053
#Sta/Elev= 30
9749.073252.79839764.527252.24459784.212253.15919794.055252.54769803.898252.9432
9810.459252.49219836.757248.49059879.705240.79619889.672 239.5579902.961237.0092
9913.045235.59579926.533232.94069964.388228.402310000.95222.196710004.67222.4497
10008.38224.259610019.45232.765810026.51236.494910030.04237.9624 10037.1239.6818
10067.84243.168410084.46245.753210101.02247.0403 10104.3247.217610128.13246.2001
10163.56247.624610186.99249.740510211.39254.722710231.42256.249510250.88258.3073
#Mann= 3 , 0 , 0
9749.073    0.12       09749.073    0.12       010250.88    0.12       0
#XS Ineff= 2 , 0
       0                               0
Bank Sta=9749.073,10250.88
Exp/Cntr=0.3,0.1

Type RM Length L Ch R = 1 ,20273.67,224.516300,224.516300,224.516300
XS GIS Cut Line= 6
1214866.49840628620877.9123593091214831.01057073620742.020571162
1214810.39082532620604.5314392971214796.89023051620546.938521851
1214777.04673135620497.8117785581214723.13758608620401.844917163
#Sta/Elev= 30
9749.043252.69169755.087251.24789778.947 249.1999794.655248.78739826.666249.7351
9890.704247.36479914.052245.85669934.064243.21679947.406242.33799967.416238.7757
9980.612231.91349990.509224.92369997.107220.8975 10000.4219.4573 10003.7219.1293
10013.61222.348710020.22223.651910050.37223.547610073.96226.336610090.92227.2723
10101.39 228.38210115.35225.193110140.54 226.05510151.81227.330110171.01228.1728
10181.92230.2156 10191.1230.778310196.97231.819110227.07233.8081 10250.9240.5453
#Mann= 3 , 0 , 0
9749.043    0.12       09749.043    0.12       0 10250.9    0.12       0
#XS Ineff= 2 , 0
       0                               0
Bank Sta=9749.043,10250.9
Exp/Cntr=0.3,0.1

Type RM Length L Ch R = 1 ,20049.15,150.413100,150.413100,150.413100
XS GIS Cut Line= 6
 1215149.0570685620604.548336392    1215047.5478 620509.96149002
1214995.95383606620484.6381781461214918.71886818620477.509636201
1214866.36097056620439.0244243441214776.14132333620301.068917081
#Sta/Elev= 30
9745.006235.99989754.195236.16869764.828234.10159810.391231.71369829.443231.2735
9855.188232.4377 9859.07232.35559906.546 225.1679921.373223.7937 9945.86220.6223
9969.417216.8558 10002.3212.676610005.58 212.87210008.86213.552710019.73216.8634
10034.74219.926510067.32222.665210071.39222.573910092.55220.283810112.15219.1157
10125.04217.758610155.01219.885910170.95  222.4310182.71225.097310190.98227.4262
10210.16233.932410221.92 237.36810232.94239.543510244.93241.070310249.55241.3382
#Mann= 3 , 0 , 0
9745.006    0.12       09745.006    0.12       010249.55    0.12       0
#XS Ineff= 2 , 0
       0                               0
Bank Sta=9745.006,10249.55
Exp/Cntr=0.3,0.1

Type RM Length L Ch R = 1 ,19898.74,187.464700,187.464700,187.464700
XS GIS Cut Line= 6
 1215130.7857207620540.6789105781214993.18692379620401.282512942
 1214979.3139604620373.6298795211214966.14791582 620311.78110552
1214948.03933747620272.5034860851214848.47622207620137.175239853
#Sta/Elev= 30
 9749.12230.54399778.726230.49449808.897229.00579815.899228.0412 9834.05223.9409
9847.664222.47939865.885 218.7179880.132216.79339893.042216.03449908.306215.8467
9934.284216.65889947.591214.70829999.746210.780210003.06210.947310006.39212.1359
10016.35 217.79610019.76218.804410023.17219.412410039.48220.8342 10064.1224.7602
10072.77225.090710086.45228.317510107.24231.500810122.93235.0903 10150.7235.0162
10162.11235.901210172.72235.043310188.26235.514610221.65235.414910250.88237.0933
#Mann= 3 , 0 , 0
 9749.12    0.12       0 9749.12    0.12       010250.88    0.12       0
#XS Ineff= 2 , 0
       0                               0
Bank Sta=9749.12,10250.88
Exp/Cntr=0.3,0.1

Type RM Length L Ch R = 1 ,19711.27,187.464800,187.464800,187.464800
XS GIS Cut Line= 6
1215285.81621789620499.2617291891215200.06134707620374.552622768
1215153.70814369620312.0088735411215130.40968635620275.222600646
1215052.26887036620196.6302750981214976.15804222620106.070294837
#Sta/Elev= 30
 9749.02241.21799763.947235.69149769.737234.23679778.327233.33959790.272232.9544
9798.235231.54429827.641221.63919838.051 218.8179846.015217.28339853.978216.9342
9869.905218.1256 9881.85 218.1739902.791215.99499926.295212.2959 9942.63210.7751
9958.965211.08119975.299212.60469998.579210.226210031.36  210.3210054.49208.8078
10096.13209.490610125.12212.240510141.67213.095110150.25214.057410175.96218.8619
10184.53219.659310218.82219.389110231.48 220.05610240.24221.093110250.89221.4415
#Mann= 3 , 0 , 0
 9749.02    0.12       0 9749.02    0.12       010250.89    0.12       0
#XS Ineff= 2 , 0
       0                               0
Bank Sta=9749.02,10250.89
Exp/Cntr=0.3,0.1

Type RM Length L Ch R = 1 ,19523.81,187.464700,187.464700,187.464700
XS GIS Cut Line= 6
1215316.62675346620408.176137087 1215245.7448782620245.380307816
1215254.12963772620129.2513466681215245.80939347620080.675680183
1215220.01429853620030.4015772391215157.51944369619951.714538409
#Sta/Elev= 30
9749.095232.94119762.451233.37289773.825231.58849781.322229.26149792.567224.9622
9807.389220.51539832.827211.89739850.122209.26189861.343208.22939871.924208.2575
 9943.72204.98979983.474204.744210000.09201.728410003.38201.840910009.97203.3197
10016.55205.8644   10033213.426410042.88216.957410056.06218.128510065.94220.5844
10075.98221.133910092.95223.353610100.08223.731810110.85223.340810148.22225.3849
10164.23224.965810172.58223.8792 10188.9224.707210243.11225.403710250.86225.0618
#Mann= 3 , 0 , 0
9749.095    0.12       09749.095    0.12       010250.86    0.12       0
#XS Ineff= 2 , 0
       0                               0
Bank Sta=9749.095,10250.86
Exp/Cntr=0.3,0.1

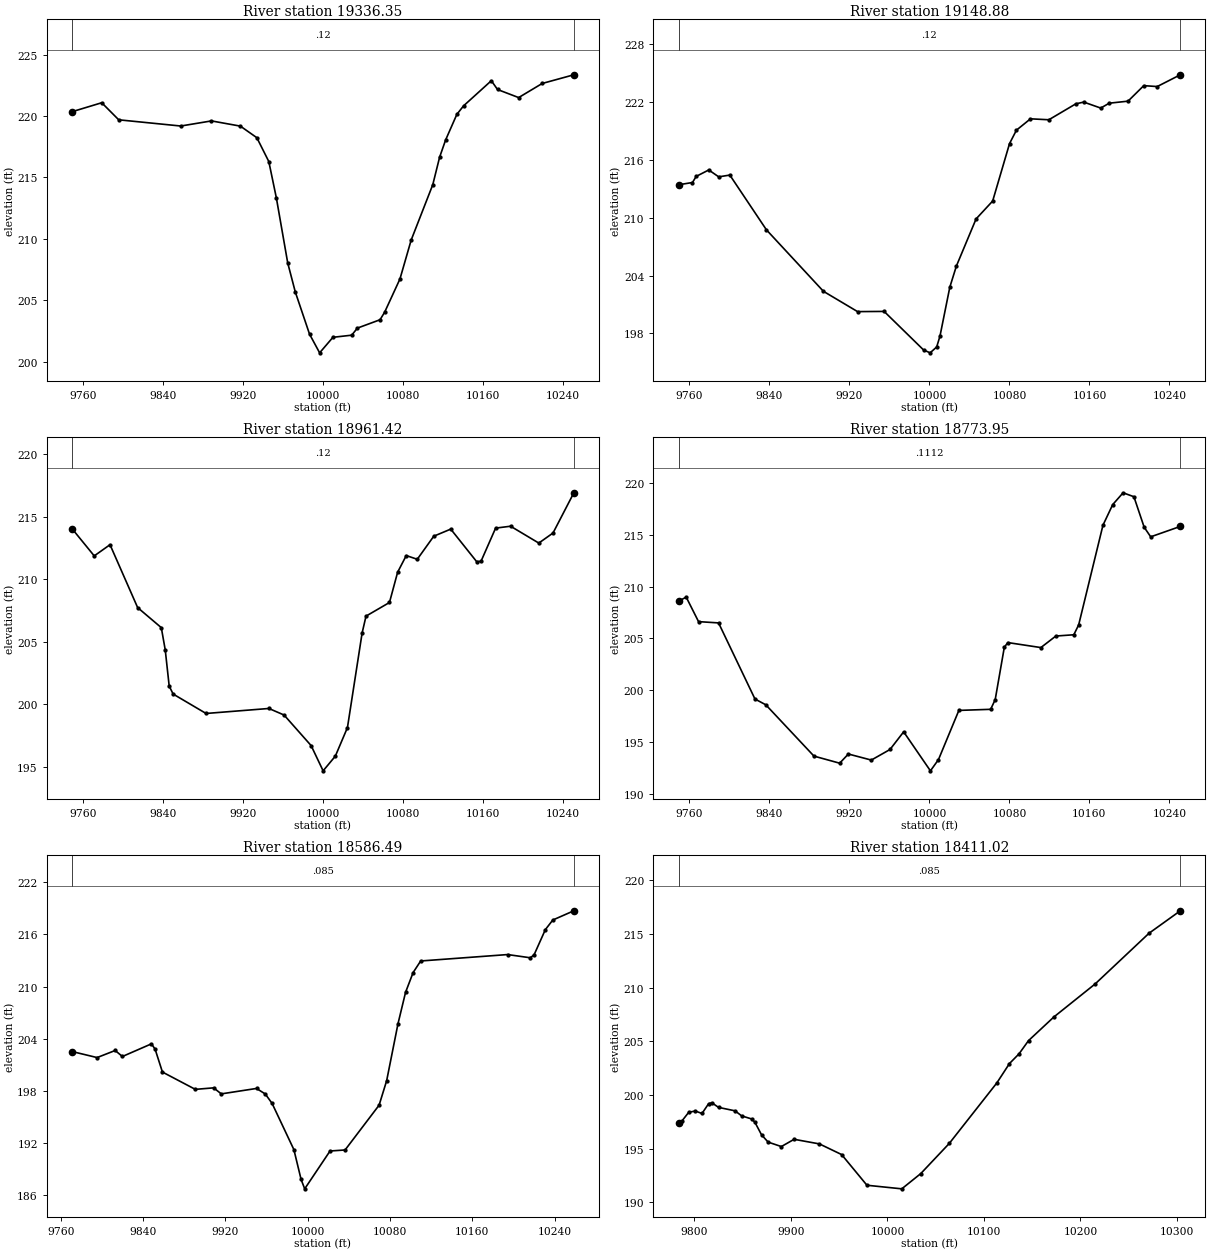
Type RM Length L Ch R = 1 ,19336.35,187.464700,187.464700,187.464700
XS GIS Cut Line= 6
1215605.38154894620330.8928788721215451.26178912620208.780760751
1215371.01147267620174.3448799481215350.80347534620149.960304185
 1215307.0100056620075.8131076481215243.21102101620000.794676277
#Sta/Elev= 30
9749.091220.35449778.749221.0846 9795.74219.69499857.769219.18989888.484219.6053
9917.371219.18079933.827218.23829945.797216.29719953.357213.33069964.697208.0445
9972.257205.6837 9986.51202.24649996.602200.724510009.91201.989610028.68 202.162
10034.33202.7374   10057203.418810061.61204.0344 10076.9206.737410088.12209.9046
10109.73214.414310116.55216.649810122.54218.0498 10133.8220.138410140.51220.8316
10168.29222.879810174.44222.162810195.58221.505210219.14222.654110250.78223.3611
#Mann= 3 , 0 , 0
9749.091    0.12       09749.091    0.12       010250.78    0.12       0
#XS Ineff= 2 , 0
       0                               0
Bank Sta=9749.091,10250.78
Exp/Cntr=0.3,0.1

Type RM Length L Ch R = 1 ,19148.88,187.464700,187.464700,187.464700
XS GIS Cut Line= 6
1215656.99435601 620092.764937521215501.74671141620021.904579839
1215372.39860086620014.8756266931215327.35816307620003.829883225
1215276.96745014 619974.735345041215204.69240883619911.495546685
#Sta/Elev= 30
9749.101 213.4069763.024213.63989766.773 214.2749779.328214.94089789.269214.2275
9800.388214.41039837.035208.73149893.993202.36639928.129200.26229954.697200.2833
9994.113196.290210000.68195.991310007.24196.599910010.52197.717310020.37202.7929
10026.93204.980210046.62209.864610063.22211.7204 10080.1 217.67510086.99219.0629
10101.05220.239310119.41220.141910146.42221.794510154.33221.972810171.29221.3537
10179.79221.859810198.59222.069410214.32223.676410227.78223.583210250.88224.8031
#Mann= 3 , 0 , 0
9749.101    0.12       09749.101    0.12       010250.88    0.12       0
#XS Ineff= 2 , 0
       0                               0
Bank Sta=9749.101,10250.88
Exp/Cntr=0.3,0.1

Type RM Length L Ch R = 1 ,18961.42,187.464700,187.464700,187.464700
XS GIS Cut Line= 6
1215712.45824634620052.9896558131215622.69336261619992.986185739
1215567.29013624619946.4038713161215531.84039881619903.973199656
1215451.33648635619786.5931594531215367.85242233619695.340784091
#Sta/Elev= 30
9749.054214.03679771.227 211.8659787.012212.75919814.637 207.7349838.315206.1307
9842.261204.34579846.207201.45629850.154200.82279883.074199.27169945.951 199.671
9961.118199.14639988.155196.705210000.17194.686810012.39195.8633 10024.5198.1457
10039.17205.702310043.07207.051510066.53208.141410074.69210.559810083.31211.8917
10094.32211.594110110.85213.438710127.82214.005510153.77 211.40210158.09 211.433
10172.69214.084810187.67214.2367 10215.9212.889410230.12213.694610250.96216.9091
#Mann= 3 , 0 , 0
9749.054    0.12       09749.054    0.12       010250.96    0.12       0
#XS Ineff= 2 , 0
       0                               0
Bank Sta=9749.054,10250.96
Exp/Cntr=0.3,0.1

Type RM Length L Ch R = 1 ,18773.95,187.464700,187.464700,187.464700
XS GIS Cut Line= 6
1215838.04728501619919.236887156 1215762.4896182619864.728440274
1215705.08982148619816.4757011741215668.41124573619780.543802996
1215562.22867308619663.7462091261215467.42231725619583.166702362
#Sta/Elev= 30
9749.056208.59019756.735208.98589769.066206.61849789.099206.49379825.508 199.139
9836.359198.57929884.519193.62039910.235192.93619918.922 193.8239941.886193.2373
9960.561194.25999974.228195.9679   10001 192.19710009.06193.283710029.45198.0375
10061.23198.143210065.79199.077710074.91204.140510078.41204.594110111.48204.1102
10126.46205.225910144.42205.347710149.28206.303210173.58215.935610183.31217.9256
10193.72219.071110204.54218.688410214.79215.744310221.32214.814210250.96215.8203
#Mann= 3 , 0 , 0
9749.056  0.1112       09749.056  0.1112       010250.96  0.1112       0
#XS Ineff= 2 , 0
       0                               0
Bank Sta=9749.056,10250.96
Exp/Cntr=0.3,0.1

Type RM Length L Ch R = 1 ,18586.49,175.470600,175.470600,175.470600
XS GIS Cut Line= 6
1215995.59780591619718.7019386641215934.06694678619695.093614812
1215805.24940437619641.5837159671215760.98620298619624.729854003
1215580.19618726619533.6471200371215550.83065449619519.936398969
#Sta/Elev= 30
9771.101202.54149795.417201.84759812.987202.66059820.015201.9712 9848.25203.4249
9851.802202.80919858.908200.18349890.881198.19489908.644198.36769916.111197.6755
9950.321198.29949958.873 197.6629965.487 196.5789986.653191.26959993.655 187.845
9997.157186.765110021.78191.113510036.39191.230410069.45196.3769 10076.8199.1925
10087.82205.740210095.17209.345610102.52211.617110109.86212.945410194.36213.6833
 10216.4213.313810220.07213.655910231.03216.553510238.27217.653510258.71218.7136
#Mann= 3 , 0 , 0
9771.101   0.085       09771.101   0.085       010258.71   0.085       0
#XS Ineff= 2 , 0
       0                               0
Bank Sta=9771.101,10258.71
Exp/Cntr=0.3,0.1

Type RM Length L Ch R = 1 ,18411.02,112.087700,112.087700,112.087700
XS GIS Cut Line= 4
1216012.56699866619493.2011415511215908.14352873619461.731054723
1215692.14429644 619457.439679251215497.60194153619468.883347169
#Sta/Elev= 30
9783.532197.43129787.274197.60579794.127198.3918 9800.98198.50439807.833198.2756
9814.686199.18749818.113199.27199824.966198.84559842.099198.52379848.952198.0522
9859.232 197.7699862.658197.46139869.512196.29459876.365195.60979890.071 195.195
9903.304 195.8719929.556195.44089952.526194.44919978.778191.589210014.87 191.255
10034.56192.6775 10064.1195.488310113.33201.118110126.47202.931510136.33203.8303
10146.19205.064610172.48207.269410215.21210.344510271.08215.071110303.51217.1647
#Mann= 3 , 0 , 0
9783.532   0.085       09783.532   0.085       010303.51   0.085       0
#XS Ineff= 2 , 0
       09804.002                       0
Bank Sta=9783.532,10303.51
Exp/Cntr=0.3,0.1

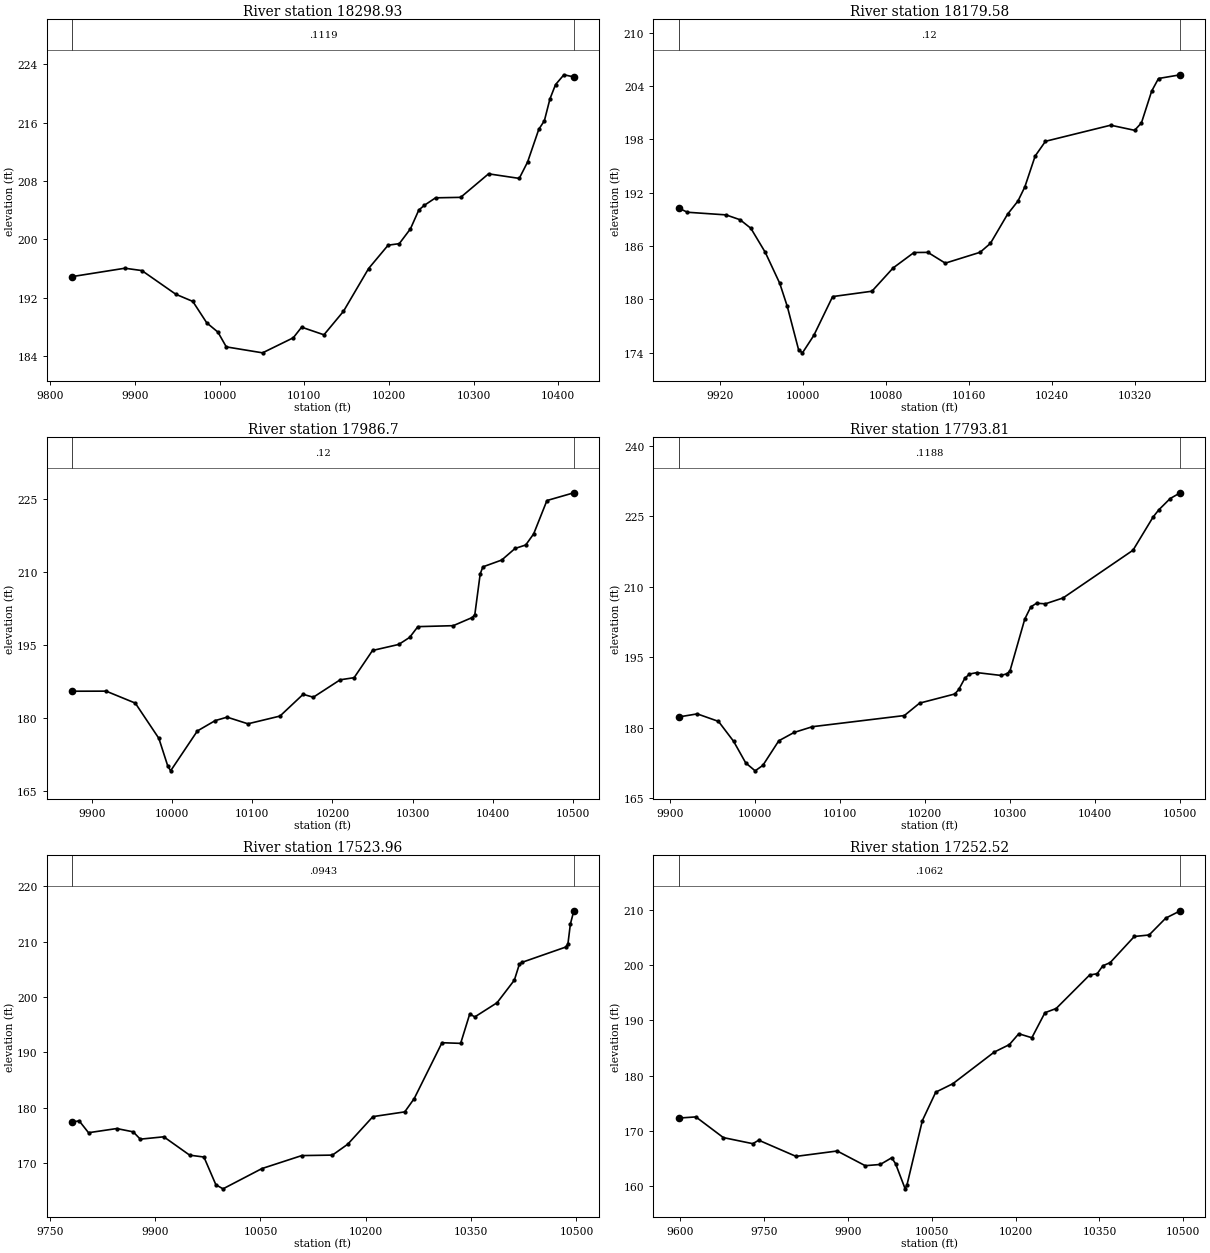
Type RM Length L Ch R = 1 ,18298.93,119.345400,119.345400,119.345400
XS GIS Cut Line= 3
1215978.23599485619371.612169713 1215842.3424381619344.433458358
1215390.31755462619385.916754633
#Sta/Elev= 30
9825.878194.91019888.203196.05949908.278195.73969948.427192.4877 9968.44191.5108
9984.914 188.5699998.092187.301110007.98185.274210050.81184.457310087.05186.5189
10096.93187.976710123.29186.930910146.35190.1526   10176196.014710199.06199.2195
10212.24199.429610225.42201.4598 10235.3204.038610241.89204.691710255.07205.7133
10284.72205.779310317.67209.003510353.91208.377110363.79210.634610376.97 215.109
10383.56216.277910390.15219.276610396.74221.236310406.62 222.58710418.39222.2948
#Mann= 3 , 0 , 0
9825.878  0.1119       09825.878  0.1119       010418.39  0.1119       0
#XS Ineff= 2 , 0
       09832.408                       0
Bank Sta=9825.878,10418.39
Exp/Cntr=0.3,0.1

Type RM Length L Ch R = 1 ,18179.58,192.886600,192.886600,192.886600
XS GIS Cut Line= 6
 1215912.2694848619193.8334498691215853.21572207619208.898929579
1215770.22702982619244.4152465831215723.82726964619258.526804804
1215533.32168375619292.7413270681215443.40323768619300.221822306
#Sta/Elev= 30
9880.062190.27939888.599189.80549925.844189.50769939.387188.96169949.781187.9998
9963.699185.28789977.616181.81119984.899179.21019995.868174.30359999.543 173.989
10010.48175.949610028.61180.317910066.49180.9196 10086.9183.536810107.03 185.274
10120.44  185.2910137.21184.078110170.74185.2987 10180.7186.300110197.29189.5932
10207.24 191.06210213.88192.650510223.83196.126810233.79 197.78710296.65199.5972
 10319.7199.022410326.28199.852210336.16203.432710342.74204.850510363.78205.2693
#Mann= 3 , 0 , 0
9880.062    0.12       09880.062    0.12       010363.78    0.12       0
#XS Ineff= 2 , 0
       0                               0
Bank Sta=9880.062,10363.78
Exp/Cntr=0.3,0.1

Type RM Length L Ch R = 1 , 17986.7,192.886600,192.886600,192.886600
XS GIS Cut Line= 6
1215841.08825399618998.5654434781215643.18079178619096.842169625
1215543.43454765 619141.394521781215424.58921943619180.087239014
1215356.99058831619195.2045089931215257.15045361619208.971531994
#Sta/Elev= 30
9875.512185.45769917.948185.47389954.313183.0166 9983.69175.77139994.683170.1509
9998.348169.099910031.69177.293410053.93179.422810068.76180.128410094.71178.7632
10134.66180.352710163.51184.8203 10176.2184.224410209.66187.804110227.07188.2421
   10250193.829210282.62195.066110296.28196.519710306.53198.725210350.62 198.925
10374.15200.591910377.52201.212510384.24209.5944 10387.6211.012210411.02212.4097
10427.66214.787910440.96215.501810450.87217.790710467.39224.636610500.95226.2289
#Mann= 3 , 0 , 0
9875.512    0.12       09875.512    0.12       010500.95    0.12       0
#XS Ineff= 2 , 0
       0                               0
Bank Sta=9875.512,10500.95
Exp/Cntr=0.3,0.1

Type RM Length L Ch R = 1 ,17793.81,269.852000,269.852000,269.852000
XS GIS Cut Line= 6
1215714.23782117618851.9683953891215614.44358455618893.695574183
1215460.67901334618963.8852712041215355.66894597619007.414840547
1215261.73811481619039.4716478681215164.04126575 619064.25154246
#Sta/Elev= 30
    9910182.27479932.024182.93749957.048181.33669974.922177.07749989.133172.4894
10000.23170.806210009.31171.973110028.08177.207510046.11178.984610067.75180.2105
10175.95182.582510193.87 185.22410235.39 187.17710240.04188.142810247.15190.5101
10252.53191.419310261.35191.728910289.77 191.12410296.87191.486510300.42192.1429
10317.77 203.13710324.81205.712810331.63206.501510342.03206.378310362.83 207.625
10445.22 217.79110468.81 224.84110475.55226.385710489.03228.806510500.95230.0272
#Mann= 3 , 0 , 0
    9910  0.1188       0    9910  0.1188       010500.95  0.1188       0
#XS Ineff= 2 , 0
       0                               0
Bank Sta=9910,10500.95
Exp/Cntr=0.3,0.1

Type RM Length L Ch R = 1 ,17523.96,271.433600,271.433600,271.433600
XS GIS Cut Line= 6
1215753.07795134618657.280031353 1215584.4087691618622.612091783
1215511.16469656618642.7762102481215435.21746292 618673.96858056
1215213.45837931618778.0001206751215082.34933053618825.134228317
#Sta/Elev= 30
9781.674177.37589791.721177.63669805.118175.47819845.311176.23169868.757175.6345
9878.806174.3129  9912.3174.73979949.143171.42529969.474171.08449986.475166.0738
9996.648165.338510052.06169.001610108.81171.347110152.43171.433110174.28173.4009
10210.11 178.38610255.45179.242810268.95181.648410308.49191.737510335.06191.6207
10348.02196.9334 10355.2196.397510386.91198.959210411.55203.043310418.58205.8822
 10422.1206.244110484.82209.023610487.88209.612210491.33213.182510496.29215.5743
#Mann= 3 , 0 , 0
9781.674  0.0943       09781.674  0.0943       010496.29  0.0943       0
#XS Ineff= 2 , 0
       0                               0
Bank Sta=9781.674,10496.29
Exp/Cntr=0.3,0.1

Type RM Length L Ch R = 1 ,17252.52,230.260600,230.260600,230.260600
XS GIS Cut Line= 6
1215742.66128463618513.1828091141215481.04866243618412.844953274
1215407.41671737618427.5254872821215292.45439914618461.691032773
1215161.02819586618492.8390777051214877.54192018618539.972676155
#Sta/Elev= 30
9596.914172.34469627.922172.55519677.116168.81179729.824167.71079740.366168.3424
9807.129165.41299880.738 166.3899930.919163.72949957.812163.95129978.359165.1635
9985.208164.083410002.36159.541310005.78160.317210033.14171.886510057.08177.0335
10087.64178.558310161.82184.290710188.79185.635110205.65187.601210229.05186.8804
10252.44191.409610272.48192.166210332.35198.225210345.93198.4641 10355.9199.8842
10369.19200.475210412.36205.200310438.84205.470610468.63208.524210494.66209.8499
#Mann= 3 , 0 , 0
9596.914  0.1062       09596.914  0.1062       010494.66  0.1062       0
#XS Ineff= 2 , 0
       0                               0
Bank Sta=9596.914,10494.66
Exp/Cntr=0.3,0.1

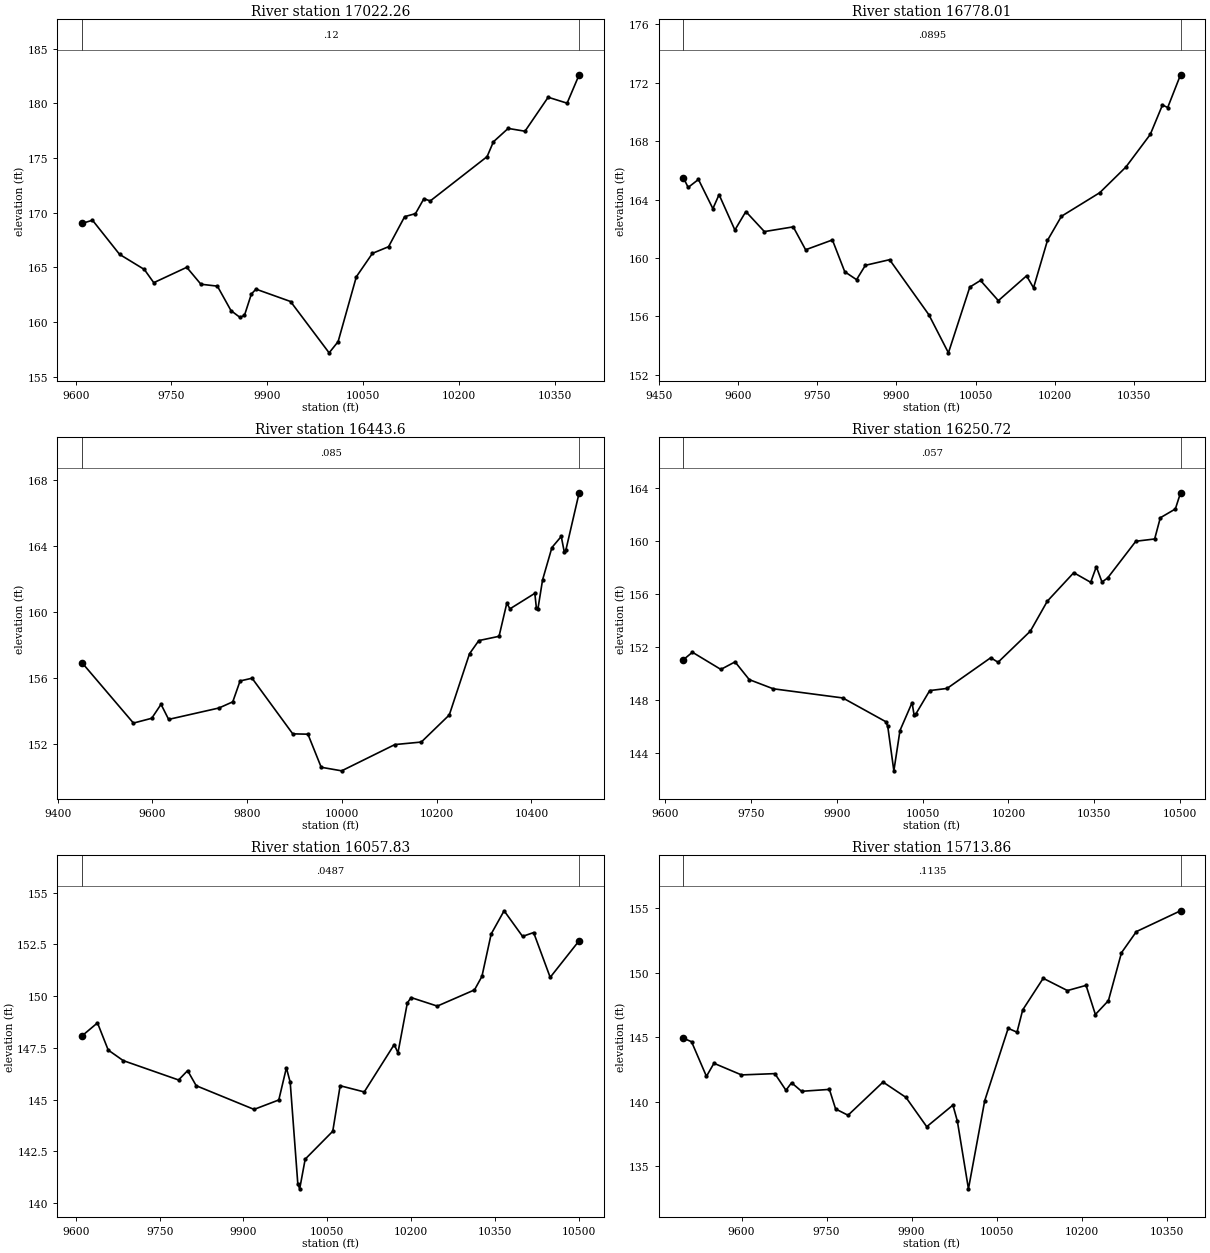
Type RM Length L Ch R = 1 ,17022.26,244.257500,244.257500,244.257500
XS GIS Cut Line= 6
1215751.34184021618405.5439202341215555.77233684618305.096577004
1215496.43450928618280.9067402931215420.81511605618239.590345204
1215292.08841127618183.7545850721215025.64739573618209.363364667
#Sta/Elev= 30
9609.916169.01229626.404169.30429668.757166.18659707.546164.80359722.299163.5952
9773.935 165.0019796.065163.45539821.883163.27999843.183161.04289857.077160.4294
9864.218160.59939875.053162.55629882.277163.00539936.381161.87559996.769 157.183
10010.86158.208710039.36164.134610064.58166.277310089.79166.883210115.01169.6332
10131.95 169.90910145.14 171.27310155.03171.066210244.02175.1174 10253.9176.4717
10276.98177.696910303.34177.4404 10339.6180.546710369.26180.003510388.12182.5996
#Mann= 3 , 0 , 0
9609.916    0.12       09609.916    0.12       010388.12    0.12       0
#XS Ineff= 2 , 0
       0                               0
Bank Sta=9609.916,10388.12
Exp/Cntr=0.3,0.1

Type RM Length L Ch R = 1 ,16778.01,334.402300,334.402300,334.402300
XS GIS Cut Line= 4
1215980.50850686618280.5439202341215678.42517352618086.099475786
1215419.74461797618023.5994757861215105.50850686618056.585586905
#Sta/Elev= 30
9496.689165.49599505.743164.82659525.252165.37079552.564163.37419564.269164.3334
9594.244 161.9129614.992163.17519650.108161.80649704.732162.12919728.142160.5623
9778.865161.23519802.275159.05849824.586 158.5199841.293   159.59887.148159.8837
9961.403156.12379998.531153.514210039.03158.011310059.28158.464310093.04157.0827
10146.48158.781410159.67157.960910186.06161.204310212.45162.851510285.03164.4661
10334.51166.219710380.69168.450310403.79170.463110413.68170.289710438.03172.5298
#Mann= 3 , 0 , 0
9496.689  0.0895       09496.689  0.0895       010438.03  0.0895       0
#XS Ineff= 2 , 0
       0 9790.85                       0
Bank Sta=9496.689,10438.03
Exp/Cntr=0.3,0.1

Type RM Length L Ch R = 1 , 16443.6,192.886500,192.886500,192.886500
XS GIS Cut Line= 6
1215907.59184018618016.6550313381215596.82795134617804.849475801
 1215483.6842472617756.9900951831215384.95768011617740.827328846
1215318.73615047617736.681119367 1214934.4942463617751.878462508
#Sta/Elev= 30
9451.054156.93689559.758153.27169598.337 153.5639618.012154.41029634.071153.4958
9740.346154.18679769.473154.56029784.946155.8267 9810.25155.9937 9896.15152.6189
9928.211152.59819956.254150.59189999.429150.375110111.81151.968510167.61152.1213
10226.71153.7644 10269.4157.4767 10289.1 158.27610331.79 158.53510348.21160.5495
10354.78160.199910407.33161.141410410.61 160.25710413.89160.201110423.75161.9637
10443.45163.920910463.15164.592110469.72163.620210473.01163.779910500.94167.2405
#Mann= 3 , 0 , 0
9451.054   0.085       09451.054   0.085       010500.94   0.085       0
#XS Ineff= 2 , 0
       09756.838                       0
Bank Sta=9451.054,10500.94
Exp/Cntr=0.3,0.1

Type RM Length L Ch R = 1 ,16250.72,192.886600,192.886600,192.886600
XS GIS Cut Line= 6
1215742.66128463617690.2661424431215584.67517352617568.738364682
1215468.63612414617544.0750397921215374.83104508617578.584465102
1215299.05390582617594.339196957 1214927.0761192 617626.79508856
#Sta/Elev= 30
9632.028151.06099647.858151.62589697.529150.32869722.364150.89779747.199149.5574
9789.027 148.8669910.741148.17259985.674146.38169989.227146.02449999.894142.6666
 10010.6145.7126 10031.7147.815310035.16146.9158 10038.4146.967710062.55  148.73
10092.88 148.89210169.17151.210110182.02150.869710238.49153.221910268.15155.4869
 10314.3157.6347 10343.9  156.9110353.76158.085610363.62156.931610373.49157.2346
10422.81160.010910455.69160.182110465.55161.783210491.86162.448910500.95163.6724
#Mann= 3 , 0 , 0
9632.028   0.057       09632.028   0.057       010500.95   0.057       0
#XS Ineff= 2 , 0
       09787.495                       0
Bank Sta=9632.028,10500.95
Exp/Cntr=0.3,0.1

Type RM Length L Ch R = 1 ,16057.83,343.971800,343.971800,343.971800
XS GIS Cut Line= 6
1215766.96684021617556.5855868911215504.81406245617396.863364682
1215426.61838445617375.1796843041215320.49355926617385.434361836
1215096.74215166 617429.194807351214930.38527433617445.832557356
#Sta/Elev= 30
9610.876148.07669638.663148.70619657.872147.39319684.765146.88369783.844145.9482
 9800.02146.40019815.387145.67089918.972144.52679963.232144.98229976.851146.5345
 9983.66145.84059997.279 140.93310000.64140.6891 10010.5142.123710059.85143.4706
10073.09145.669610116.25145.370310169.88147.659510176.59147.260110193.35149.6686
10200.05149.929410246.96149.516910313.57150.299210326.89150.949910343.46153.0014
 10366.6154.121510399.64152.884410419.47 153.069 10449.1150.904910500.95152.6748
#Mann= 3 , 0 , 0
9610.876  0.0487       09610.876  0.0487       010500.95  0.0487       0
#XS Ineff= 2 , 0
       09795.643                       0
Bank Sta=9610.876,10500.95
Exp/Cntr=0.3,0.1

Type RM Length L Ch R = 1 ,15713.86,234.687900,234.687900,234.687900
XS GIS Cut Line= 6
1215690.57795134617395.127253562 1215530.8557291617218.043920234
1215372.17741513617140.5005667511215347.95136836617128.133504212
1215223.72003698617048.0130787041214937.10572907617028.807809114
#Sta/Elev= 30
9497.263144.91869511.711144.64249537.992141.95789551.246 142.9729599.847142.0691
9658.665142.17039678.259140.87949688.211141.46049705.884140.79889754.967 140.946
9765.922139.42889787.831138.9413 9849.64141.51549890.077140.32529926.718138.0515
9972.954139.72939980.799138.477510000.34133.232710029.04140.069110070.44145.6841
10086.02145.383210096.09147.112510132.27 149.56510175.01148.612610207.89 149.015
10224.33146.755610247.35147.831110270.37151.545810296.67153.187210374.64154.8016
#Mann= 3 , 0 , 0
9497.263  0.1135       09497.263  0.1135       010374.64  0.1135       0
#XS Ineff= 2 , 0
       09617.981                       0
Bank Sta=9497.263,10374.64
Exp/Cntr=0.3,0.1

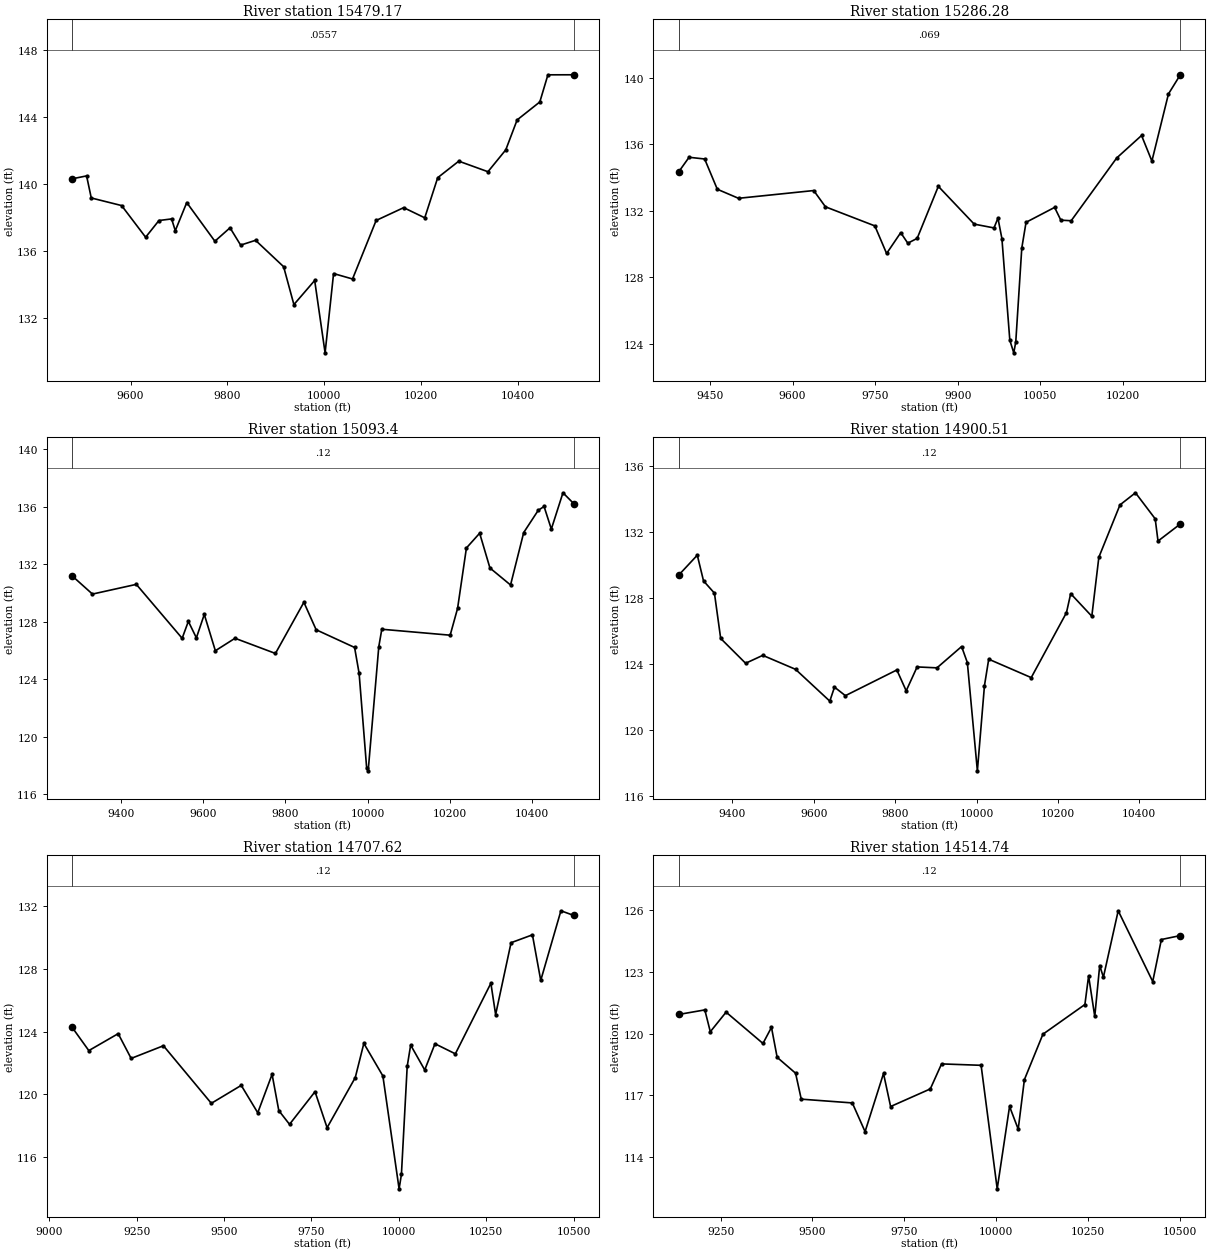
Type RM Length L Ch R = 1 ,15479.17,192.886600,192.886600,192.886600
XS GIS Cut Line= 6
  1215825.994618617292.6966980251215587.54968351617035.492279872
1215551.79571939617013.2974339571215514.01196375616983.390965536
1215400.85705492616862.9160909951214978.77239573616775.335586891
#Sta/Elev= 30
9479.035140.33099509.073140.50569518.725139.1891 9581.46 138.7369631.132136.8467
9658.672137.84399684.818137.93919692.452137.23739716.134 138.9159774.294136.6086
 9805.61137.40989827.574136.37639858.386136.66299916.401 135.0899937.669132.8293
9980.619134.267910002.16129.950610019.69134.680510058.89134.356110107.66137.8466
10164.63138.611510208.19138.005410234.99140.398610278.55141.384610338.86140.7548
10375.72142.059410399.18143.844210446.09144.916910462.84146.535110516.48146.5375
#Mann= 3 , 0 , 0
9479.035  0.0557       09479.035  0.0557       010516.48  0.0557       0
#XS Ineff= 2 , 0
       09625.355                       0
Bank Sta=9479.035,10516.48
Exp/Cntr=0.3,0.1

Type RM Length L Ch R = 1 ,15286.28,192.886600,192.886600,192.886600
XS GIS Cut Line= 6
1216049.95295134617129.5022535771215685.36961797616825.682809129
1215565.29362011616771.8838962471215563.43972647616771.133510798
1215535.97789079616758.0056848081215297.91662239616624.830583834
#Sta/Elev= 30
9392.842134.32929412.005135.21849440.275135.11439463.253133.29469501.773132.7503
9638.352133.21679659.705 132.238 9749.39131.09069770.743129.42989796.367 130.683
9809.263130.04929826.262130.34039864.698133.46969929.841 131.1979965.791130.9682
9972.982131.55559980.172130.32639994.552124.206610001.72123.453910005.36 124.116
10016.26129.755210024.01131.3056 10075.9 132.20310087.18131.435310105.98131.4004
10188.68135.176810233.79136.528110252.59134.990110282.66139.028610304.22140.1807
#Mann= 3 , 0 , 0
9392.842   0.069       09392.842   0.069       010304.22   0.069       0
#XS Ineff= 2 , 0
       0 9586.31                       0
Bank Sta=9392.842,10304.22
Exp/Cntr=0.3,0.1

Type RM Length L Ch R = 1 , 15093.4,192.886500,192.886500,192.886500
XS GIS Cut Line= 6
1216266.96684018616957.6272535771215770.94216672616655.073058516
1215690.43082222616620.1712128971215591.88753158616570.526792809
 1215440.6635868616502.0966877941215187.15415096616396.454977274
#Sta/Elev= 30
9281.211131.20069330.783129.93029437.364130.60679548.811126.85369563.898 128.032
9583.398126.88319602.613 128.5169629.513 125.9879677.306126.85589775.547125.7992
9844.721129.35959874.544127.4474 9967.97126.21599978.975124.41569997.317117.8255
   10001117.630710026.77126.263410034.12127.483410200.29127.0696 10218.3 128.931
10239.81133.139110271.98134.164810297.01131.745310347.07130.563110379.07134.2123
10414.41135.759510428.55136.027110446.22134.453310474.49136.979510500.98136.2175
#Mann= 3 , 0 , 0
9281.211    0.12       09281.211    0.12       010500.98    0.12       0
#XS Ineff= 2 , 0
       09515.701                       0
Bank Sta=9281.211,10500.98
Exp/Cntr=0.3,0.1

Type RM Length L Ch R = 1 ,14900.51,192.886600,192.886600,192.886600
XS GIS Cut Line= 6
1216350.30017352616790.9605868911215772.17517352616442.002253562
1215719.92202047616421.261142924 1215718.0303762616420.611772537
1215586.27155489616373.5782846211215245.06481075616258.518168792
#Sta/Elev= 30
9267.503 129.3929313.616130.61119328.945129.0506 9355.77 128.3099371.099125.5643
9432.414124.05779474.568124.53869555.043123.69239639.351121.76279650.848122.6117
9677.673122.09459804.134123.65269827.127122.38779853.953123.83679902.816123.7806
9963.326125.07289977.445124.1003 10002.1117.536910019.52122.701110029.97124.3052
10134.48123.189310221.08127.125310231.47128.2781 10283.4126.908810300.71130.4866
10352.65133.659610390.73134.394410439.21132.815510446.13131.467110500.99132.5031
#Mann= 3 , 0 , 0
9267.503    0.12       09267.503    0.12       010500.99    0.12       0
#XS Ineff= 2 , 0
       0 9444.28                       0
Bank Sta=9267.503,10500.99
Exp/Cntr=0.3,0.1

Type RM Length L Ch R = 1 ,14707.62,192.886600,192.886600,192.886600
XS GIS Cut Line= 6
1216545.19220376616732.7410812821216393.22905377616580.864435181
1215855.50850686616254.5022535621215816.69653612616242.282966286
1215662.89368844616216.0996117741215280.94983009616115.889751598
#Sta/Elev= 30
9065.437124.27889113.346122.78739197.339123.86929234.447122.28719326.791123.0977
9463.853119.41919549.386120.56589596.642118.81599637.656121.26979656.845118.9556
9687.548118.07649760.467120.16279795.007117.86169875.602121.0631 9900.16123.2474
9954.597121.168510001.01113.956410007.63114.873210024.17121.776810034.09123.1403
 10074.3121.550710103.68123.223810161.95122.581210263.58127.089410277.16125.0883
10321.31129.679110382.44130.182110406.21127.271110463.94131.719110500.97131.4191
#Mann= 3 , 0 , 0
9065.437    0.12       09065.437    0.12       010500.97    0.12       0
#XS Ineff= 2 , 0
       09338.242                       0
Bank Sta=9065.437,10500.97
Exp/Cntr=0.3,0.1

Type RM Length L Ch R = 1 ,14514.74,192.886600,192.886600,192.886600
XS GIS Cut Line= 6
1216558.63350689616481.9328091291215885.60083032616065.074100584
1215815.72786266616048.5728872421215813.78225023616048.109646246
 1215632.0914093616007.3015055211215325.34146947615941.258487806
#Sta/Elev= 30
9135.533120.92779207.057121.15019221.992120.08879264.944121.04129365.282119.5199
9388.437120.30199403.874118.84589454.043118.0737 9469.48116.8129 9608.41116.6295
9643.142115.23429693.311118.05979712.607116.45459820.664117.31019851.297118.5262
9958.868118.457710002.69112.454210036.31116.457210059.85115.354110076.67117.7604
 10127.1119.968910241.33121.412110251.39122.802710268.17120.8304 10281.6123.3065
10291.67122.740910331.94125.967910425.91122.5273 10449.4124.5707   10501124.7629
#Mann= 3 , 0 , 0
9135.533    0.12       09135.533    0.12       0   10501    0.12       0
#XS Ineff= 2 , 0
       09244.165                       0
Bank Sta=9135.533,10501
Exp/Cntr=0.3,0.1