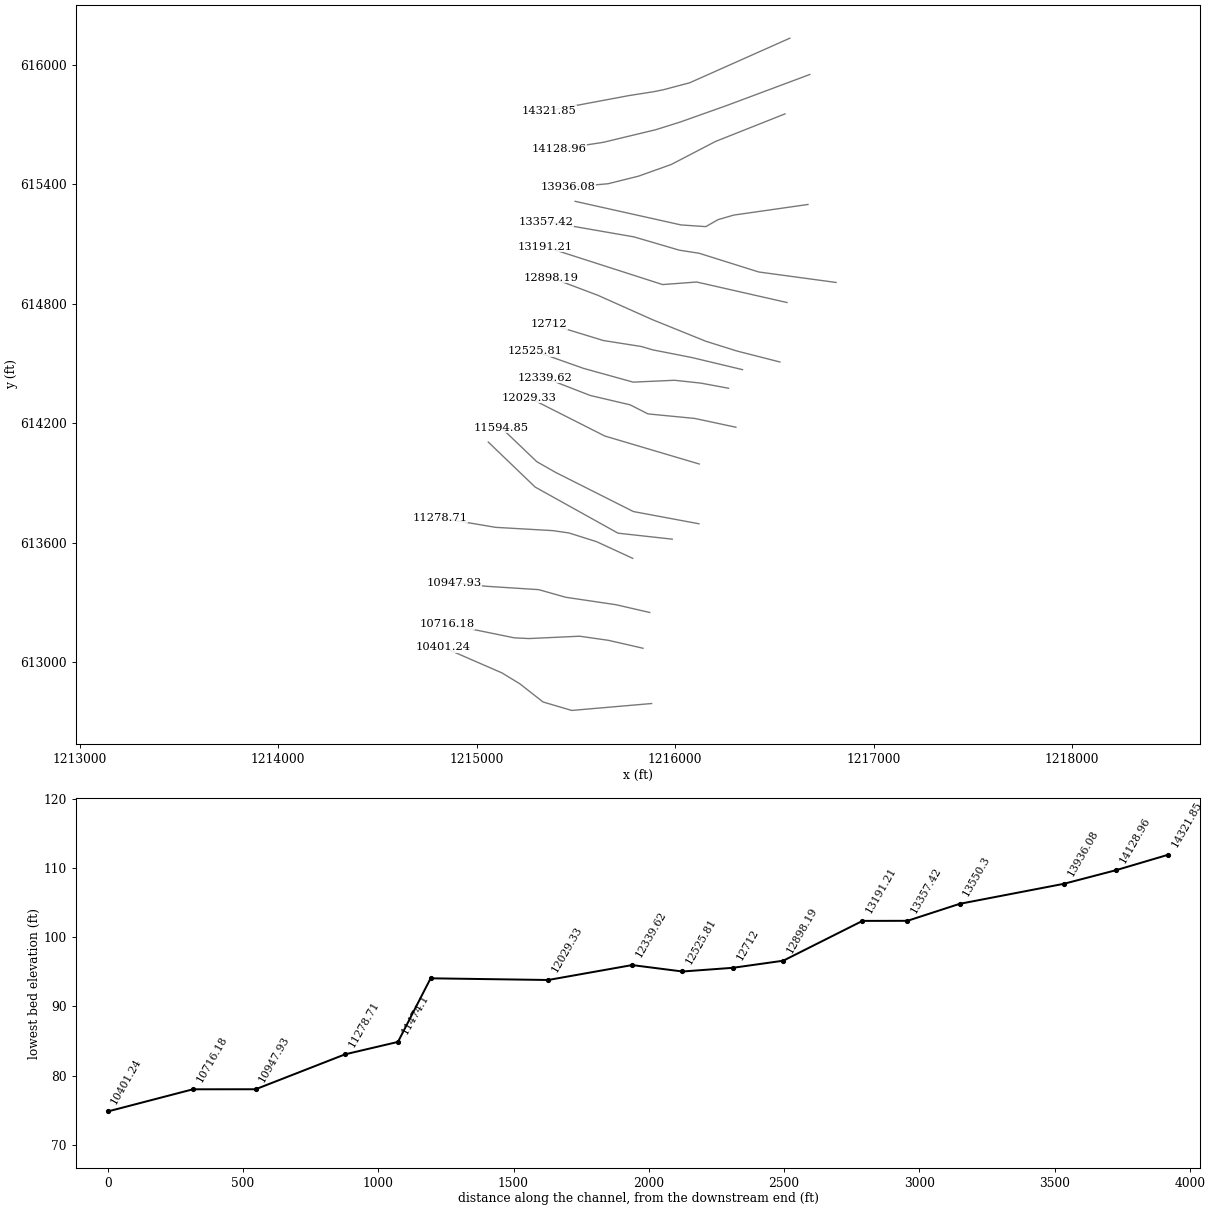
HEC-RAS study 76_ras.prj: 76

--- 76_ras.g01 (geometry) --- (continued)

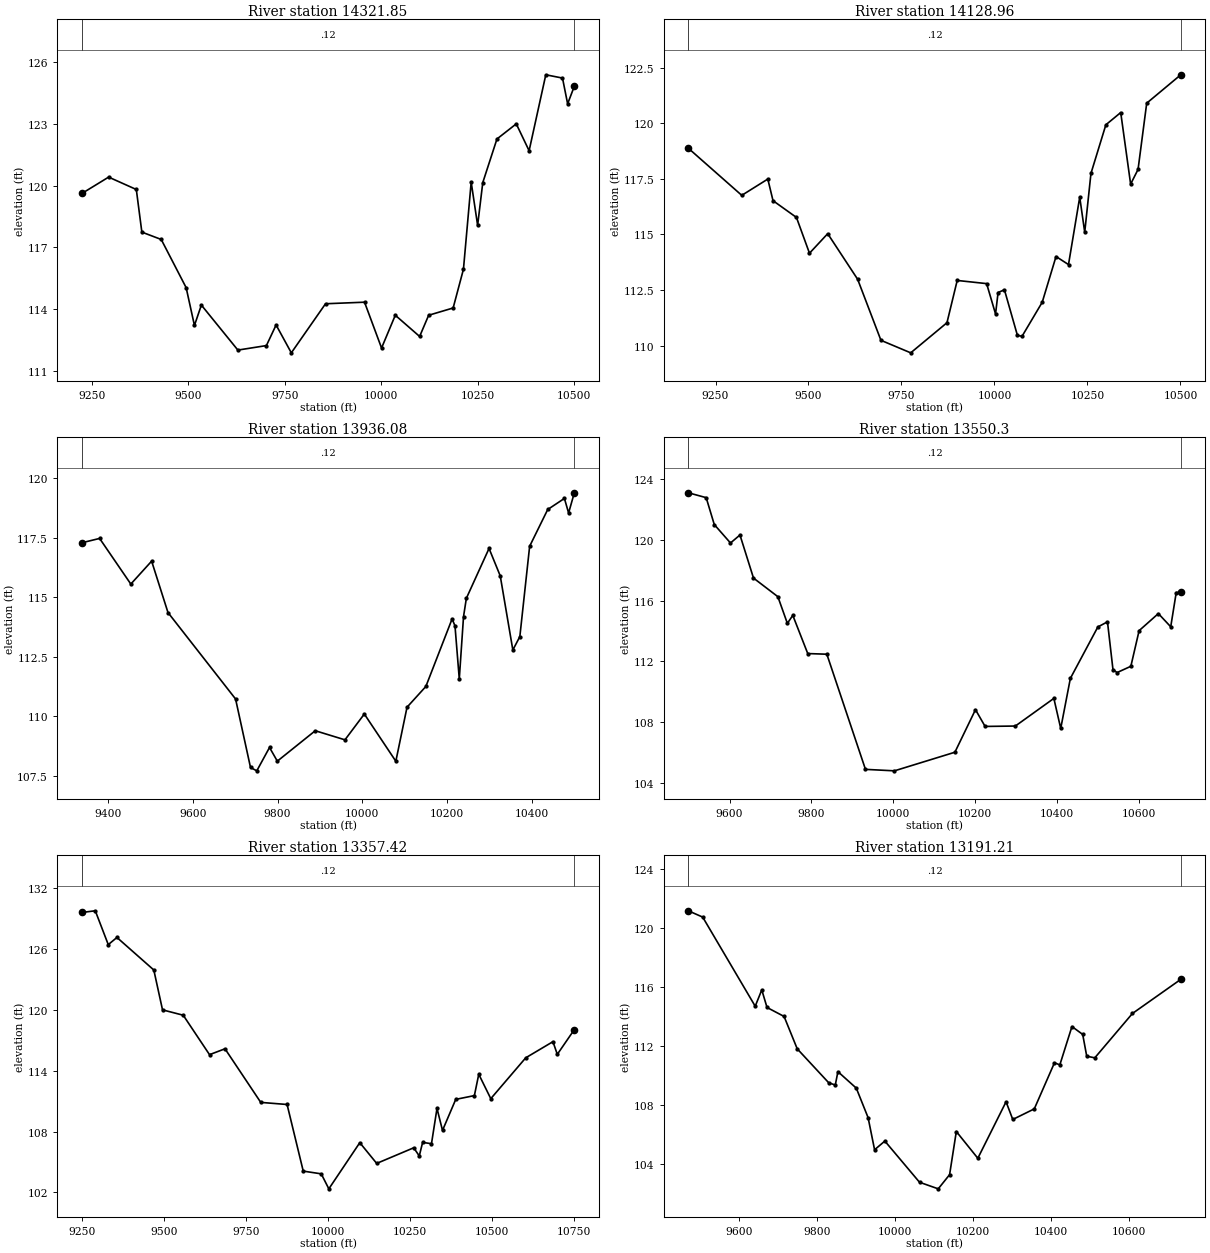
Type RM Length L Ch R = 1 ,14321.85,192.886500,192.886500,192.886500
XS GIS Cut Line= 6
1216577.73072907616134.7105869051216072.97203827615910.655519098
1215941.27284759615875.8755341321215892.23586869 615865.99149625
1215768.16078356615846.6142811331215361.97374079615770.701729342
#Sta/Elev= 30
 9223.67119.61479293.143120.40819364.933119.80829379.292117.74459429.545117.3884
9494.156115.05629515.694113.22499533.641114.21119628.345112.03159702.349112.2499
9727.476113.24819766.961111.89829855.677114.27499956.855 114.351   10001112.1314
10036.62 113.71910099.76112.691410123.16113.718210186.67114.070710213.41115.9479
10233.47120.163510250.18118.073510263.55 120.14410300.32122.254810350.39122.9866
 10383.7121.6855   10427125.3635 10470.3125.204210483.63123.957410500.98124.8073
#Mann= 3 , 0 , 0
 9223.67    0.12       0 9223.67    0.12       010500.98    0.12       0
#XS Ineff= 2 , 0
       0                               0
Bank Sta=9223.67,10500.98
Exp/Cntr=0.3,0.1

Type RM Length L Ch R = 1 ,14128.96,192.886600,192.886600,192.886600
XS GIS Cut Line= 6
1216678.42517355615952.4189202341216260.35117802615796.710079685
1216025.76282933 615713.621837781215902.55874863615675.070344806
1215637.51092842615611.5708865821215412.86112604615576.991141051
#Sta/Elev= 30
9176.905118.88119320.607116.75949390.626117.4923 9404.63116.51929467.648115.7646
9502.658114.15379551.672115.03379632.142112.98159694.791110.23369774.844109.6701
9872.295111.02529899.842112.92869978.928112.785810002.91111.420110009.73112.3859
10026.79112.508710061.82110.450610074.32  110.42 10128.4111.946810165.51114.0063
10199.06113.643510229.26116.677410242.68115.099310259.45117.747710299.51119.9347
10339.46120.4862 10366.1117.264710386.07117.926510409.32120.907710500.97122.1864
#Mann= 3 , 0 , 0
9176.905    0.12       09176.905    0.12       010500.97    0.12       0
#XS Ineff= 2 , 0
       0                               0
Bank Sta=9176.905,10500.97
Exp/Cntr=0.3,0.1

Type RM Length L Ch R = 1 ,13936.08,385.773100,385.773100,385.773100
XS GIS Cut Line= 6
1216553.42517352615754.5022535771216203.28187364615615.987554595
1215980.26630682615500.3263164611215816.08869216615441.922698468
1215662.20858374615403.6621527371215460.69170195 615385.58291094
#Sta/Elev= 30
9337.621 117.2819379.564117.46339453.295115.5464 9502.45116.50939541.071114.3503
 9700.73110.71939736.017107.8411 9750.85107.70089780.907108.68219799.358108.1073
9888.984109.38579959.109109.003410004.85110.0879 10079.3108.103910105.72110.3736
10150.22 111.24510212.18114.082910219.01113.792110229.16111.5609 10239.2114.1814
 10245.9114.949410299.47117.042710325.92115.889910355.68112.776810372.21113.3394
10395.36117.134410438.09118.679310477.52 119.14410487.38118.532310500.91119.3812
#Mann= 3 , 0 , 0
9337.621    0.12       09337.621    0.12       010500.91    0.12       0
#XS Ineff= 2 , 0
       0                               0
Bank Sta=9337.621,10500.91
Exp/Cntr=0.3,0.1

Type RM Length L Ch R = 1 , 13550.3,192.886600,192.886600,192.886600
XS GIS Cut Line= 6
1216669.16447918615299.5199311081216295.08122047615246.170908353
1216215.68021576615223.0834866921216154.42611424615188.217883939
1216029.71358037615196.6678362571215496.13350686615315.266142443
#Sta/Elev= 30
9499.111123.10499542.765122.78369562.573121.01349602.188119.79929625.336120.3261
9658.428117.49069717.994116.26489741.211114.50939754.497115.03569791.033112.5217
9837.706112.47919932.093104.899410002.95104.802310150.72106.027310201.01108.8286
10224.53107.725310298.47107.751210392.58109.570110409.38107.592410432.91110.8874
10500.13114.273910523.65114.6107 10537.1111.463710547.18111.271810580.79111.6841
10600.95  114.0310648.01115.153410678.25114.2845 10691.7116.540710702.85 116.567
#Mann= 3 , 0 , 0
9499.111    0.12       09499.111    0.12       010702.85    0.12       0
#XS Ineff= 2 , 0
       0                               0
Bank Sta=9499.111,10702.85
Exp/Cntr=0.3,0.1

Type RM Length L Ch R = 1 ,13357.42,166.209700,166.209700,166.209700
XS GIS Cut Line= 6
1216810.81166448614907.7644976511216421.44557582614960.317519101
1216120.71786775615054.4467582781216021.13824118615069.865502908
1215792.19471433615136.7303501371215347.42119516615213.761596676
#Sta/Elev= 30
9250.101129.61339290.983129.78059330.555126.44049356.936127.14919469.263 123.938
9495.765120.00749558.836119.47739638.923115.58679686.017 116.1679794.938110.8795
 9875.13110.67199924.318104.10029979.127103.831110002.27102.351610096.55106.9053
10148.04104.859310260.72106.4002 10277.7105.595410287.89106.933910314.87106.8036
10331.66110.284110348.44108.112610388.73111.175910445.51111.549110458.86113.6545
10495.49111.246710601.88115.275710684.78116.869510698.04115.617710749.89118.0605
#Mann= 3 , 0 , 0
9250.101    0.12       09250.101    0.12       010749.89    0.12       0
#XS Ineff= 2 , 0
       0                               0
Bank Sta=9250.101,10749.89
Exp/Cntr=0.3,0.1

Type RM Length L Ch R = 1 ,13191.21,293.014400,293.014400,293.014400
XS GIS Cut Line= 4
 1216563.2935181614807.0191214681216108.40771765614910.012132913
1215936.75269857614897.1380064791215343.11242437615087.388985917
#Sta/Elev= 30
  9470.6121.18999507.447120.76089642.002 114.7199658.822115.82629672.277114.6351
9716.008 114.0269749.646111.83199830.379109.53059847.199109.37769853.927110.2839
9901.021109.16669931.296107.16489947.871  104.999974.192105.578310063.02102.7869
10110.97102.340210140.09103.300410157.31106.226710212.44104.412510284.79108.2423
10302.01107.042710357.14 107.76110408.81110.884210422.59110.7448 10453.6113.3422
10481.16112.8087 10491.5111.332410512.17111.220910608.64114.228210732.52116.5408
#Mann= 3 , 0 , 0
  9470.6    0.12       0  9470.6    0.12       010732.52    0.12       0
#XS Ineff= 2 , 0
       0                               0
Bank Sta=9470.6,10732.52
Exp/Cntr=0.3,0.1

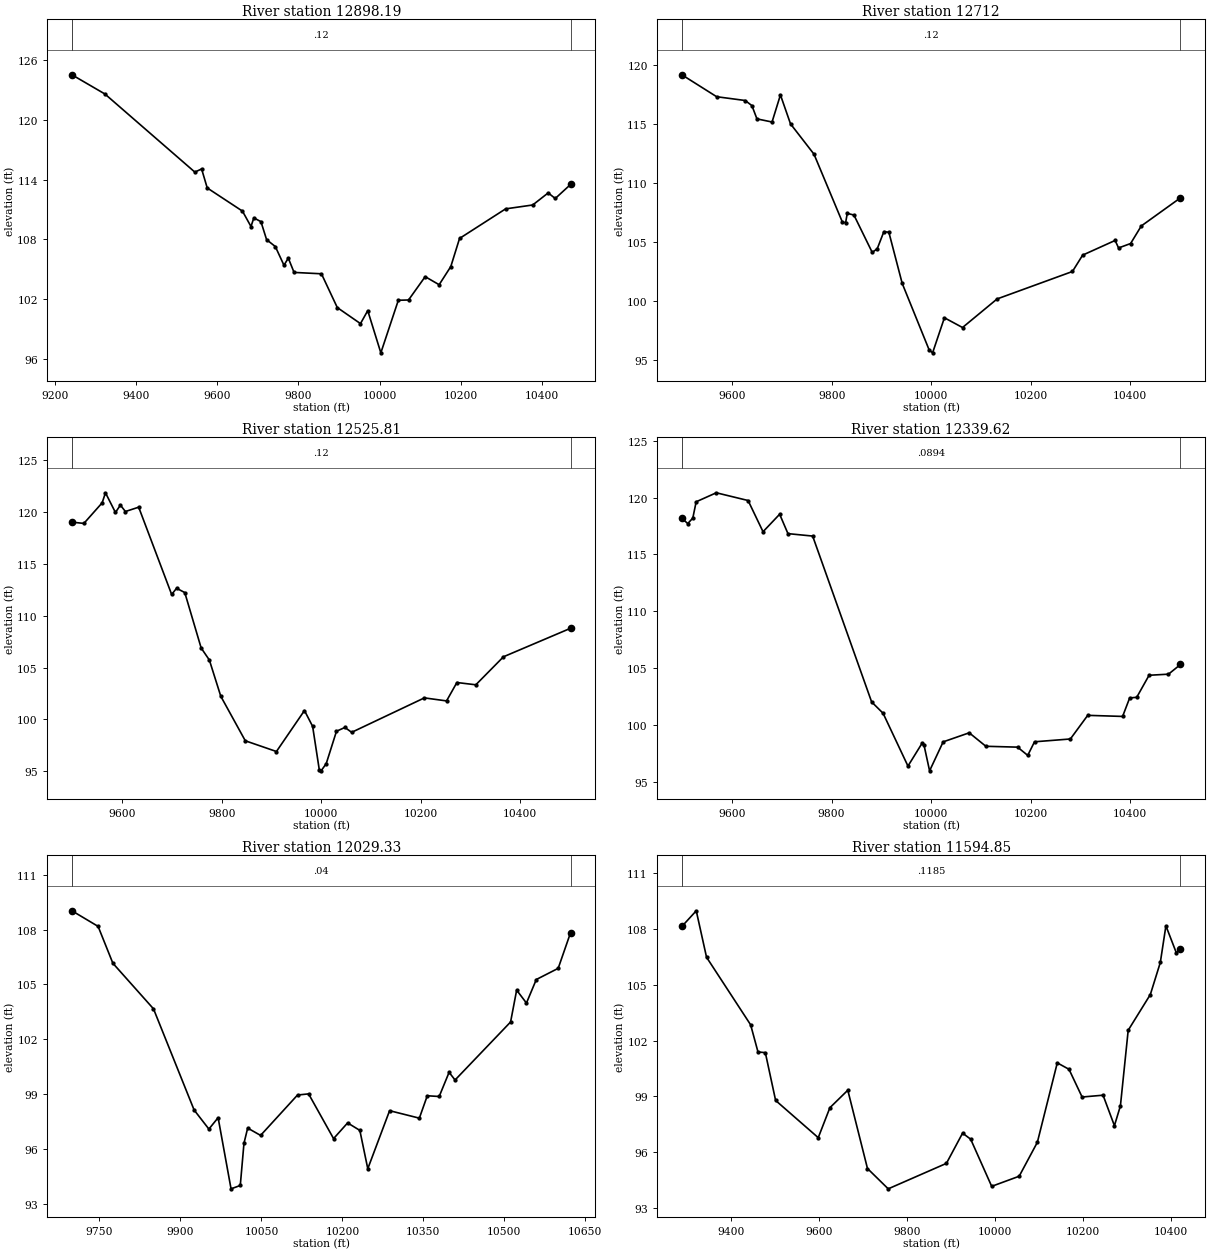
Type RM Length L Ch R = 1 ,12898.19,186.192600,186.192600,186.192600
XS GIS Cut Line= 6
1216527.72521033614508.2924879841216312.71776986614562.973459924
1216154.91516675614612.200025201 1215884.8091715614721.220133408
1215610.66829727614843.2090274811215376.26086629614931.455364387
#Sta/Elev= 30
9241.534124.53189322.939122.59939544.563114.75219561.262115.06779575.086113.1588
9661.937110.82989682.959109.28139689.967110.14959707.485109.77299721.449107.9616
9742.956107.2697 9764.27105.38889774.927106.10819789.136104.67049856.631104.5327
9895.707101.13719952.841 99.52499970.765100.829910003.0596.5886210046.17101.8717
10071.32101.899910112.33104.244210146.77103.434310175.52105.262210197.07108.0851
10310.63111.057110377.39111.446610415.59112.661610432.95112.098710470.64113.5062
#Mann= 3 , 0 , 0
9241.534    0.12       09241.534    0.12       010470.64    0.12       0
#XS Ineff= 2 , 0
       0                               0
Bank Sta=9241.534,10470.64
Exp/Cntr=0.3,0.1

Type RM Length L Ch R = 1 ,   12712,186.192700,186.192700,186.192700
XS GIS Cut Line= 6
1216339.46063758614469.8236522311216083.90953689614530.658506318
1215886.52864997614569.2898981241215830.05401196614585.959130927
1215638.69857878614615.9904164531215365.89432976 614699.26274002
#Sta/Elev= 30
9499.057119.20279568.967117.3377  9626.3117.0161 9639.79116.58099649.907115.4543
 9680.26115.18769697.123117.49129717.358115.03029764.548112.45329821.381106.6997
9828.067106.6232 9831.41107.42239844.782107.27939881.556104.10349891.585104.4109
9904.958105.87029914.987105.81529941.731101.4732 9995.9495.8121810002.8495.56632
 10026.698.5477710062.9897.7182310132.48100.148410283.84102.481310304.34103.8721
10369.58105.120110376.49104.482210400.68104.857710422.17106.351210500.91108.7428
#Mann= 3 , 0 , 0
9499.057    0.12       09499.057    0.12       010500.91    0.12       0
#XS Ineff= 2 , 0
       0                               0
Bank Sta=9499.057,10500.91
Exp/Cntr=0.3,0.1

Type RM Length L Ch R = 1 ,12525.81,186.192600,186.192600,186.192600
XS GIS Cut Line= 6
1216268.85962092614376.3514070271216128.95123812614402.198775146
1215996.79470539614416.4360981681215788.58485917 614407.05717276
1215538.51710068614476.1538428611215295.16059911 614562.00406292
#Sta/Elev= 30
9499.153119.04699523.209118.92339559.909120.91029566.581121.8817  9586.6119.9818
9596.609120.69029606.618120.07249633.309120.4903 9699.56112.0621 9709.47112.6613
9725.933112.2458 9758.86106.89229775.321105.73239798.303102.2302 9847.5397.93381
9910.09296.898159966.381100.85379982.802 99.32979996.36995.075989999.81495.03212
10010.1695.7312410030.7298.8550310047.6899.2219510061.2298.7503110207.33102.0768
10251.89101.784210272.65 103.561 10310.7103.340510366.24106.045910500.98108.7964
#Mann= 3 , 0 , 0
9499.153    0.12       09499.153    0.12       010500.98    0.12       0
#XS Ineff= 2 , 0
       0                               0
Bank Sta=9499.153,10500.98
Exp/Cntr=0.3,0.1

Type RM Length L Ch R = 1 ,12339.62,310.288500,310.288500,310.288500
XS GIS Cut Line= 6
1216305.97636305614180.5283781491216099.32415214614224.611068619
1215863.26863044614247.4530693921215772.41203732614293.257008699
1215572.32164259614340.0494659791215343.64498833614428.540505946
#Sta/Elev= 30
9499.153118.18359511.029  117.729521.141118.20399527.882119.6381 9568.33120.4306
9632.196119.74979662.235117.00229695.611118.54299712.284116.83559761.907 116.621
9880.391102.02329903.406101.02559953.37396.378319981.61498.379549985.41698.26663
9996.82395.9593510024.0798.5087610076.4399.3064810109.9198.1202410173.5898.04475
   1019497.3189110207.6298.5152410279.6698.76383 10314.5100.843310384.59100.7479
10398.77 102.37410412.95102.430510437.77104.370410476.77104.466610500.86105.3194
#Mann= 3 , 0 , 0
9499.153  0.0894       09499.153  0.0894       010500.86  0.0894       0
#XS Ineff= 2 , 0
       0                               0
Bank Sta=9499.153,10500.86
Exp/Cntr=0.3,0.1

Type RM Length L Ch R = 1 ,12029.33,434.482000,434.482000,434.482000
XS GIS Cut Line= 3
1216121.13350686613995.8216980251215645.43906245 614136.44669801
1215263.49461797614329.155031338
#Sta/Elev= 30
9698.925109.03559747.448108.18089774.818106.16159850.084103.6643 9925.3598.12369
9952.71997.079789969.82597.702479993.77493.8057710010.8893.9903810017.72 96.2999
10024.5697.1338510048.5196.7325810116.9498.9435910137.4699.0068110183.7496.55674
10209.7597.4167910232.4297.0069310247.1294.9073810287.54 98.086410342.6697.67681
10357.3698.9035710379.41 98.863410397.78100.187710408.8199.76629 10511.7 102.944
10522.94104.6896 10541.1103.981110559.35105.2704 10599.9105.882710622.78107.8315
#Mann= 3 , 0 , 0
9698.925    0.04       09698.925    0.04       010622.78    0.04       0
#XS Ineff= 2 , 0
       0                               0
Bank Sta=9698.925,10622.78
Exp/Cntr=0.3,0.1

Type RM Length L Ch R = 1 ,11594.85,120.747600,120.747600,120.747600
XS GIS Cut Line= 5
1216119.85138556613695.5528731351215789.41547388613757.062588274
1215398.90030554613953.0354017021215303.05958661614007.392824382
1215122.82181659614179.047843441
#Sta/Elev= 30
9289.402108.11259322.081108.95389345.441106.46319445.557102.84139462.243101.3864
9478.929101.34939502.28998.786689599.06796.791719625.51498.398439666.16999.33497
9710.84895.138229757.93894.049179890.086 95.41449926.79497.034529945.14796.71085
9992.86794.1829310055.27 94.724610096.5696.54365 10141.8100.8015 10168.4100.4574
10198.15  98.97110245.7299.0682710271.5597.4343110285.1498.4961810302.81102.5495
 10353.1104.464710375.75106.184410388.44108.147410412.22106.692310421.53 106.923
#Mann= 3 , 0 , 0
9289.402  0.1185       09289.402  0.1185       010421.53  0.1185       0
#XS Ineff= 2 , 0
       0                               0
Bank Sta=9289.402,10421.53
Exp/Cntr=0.3,0.1

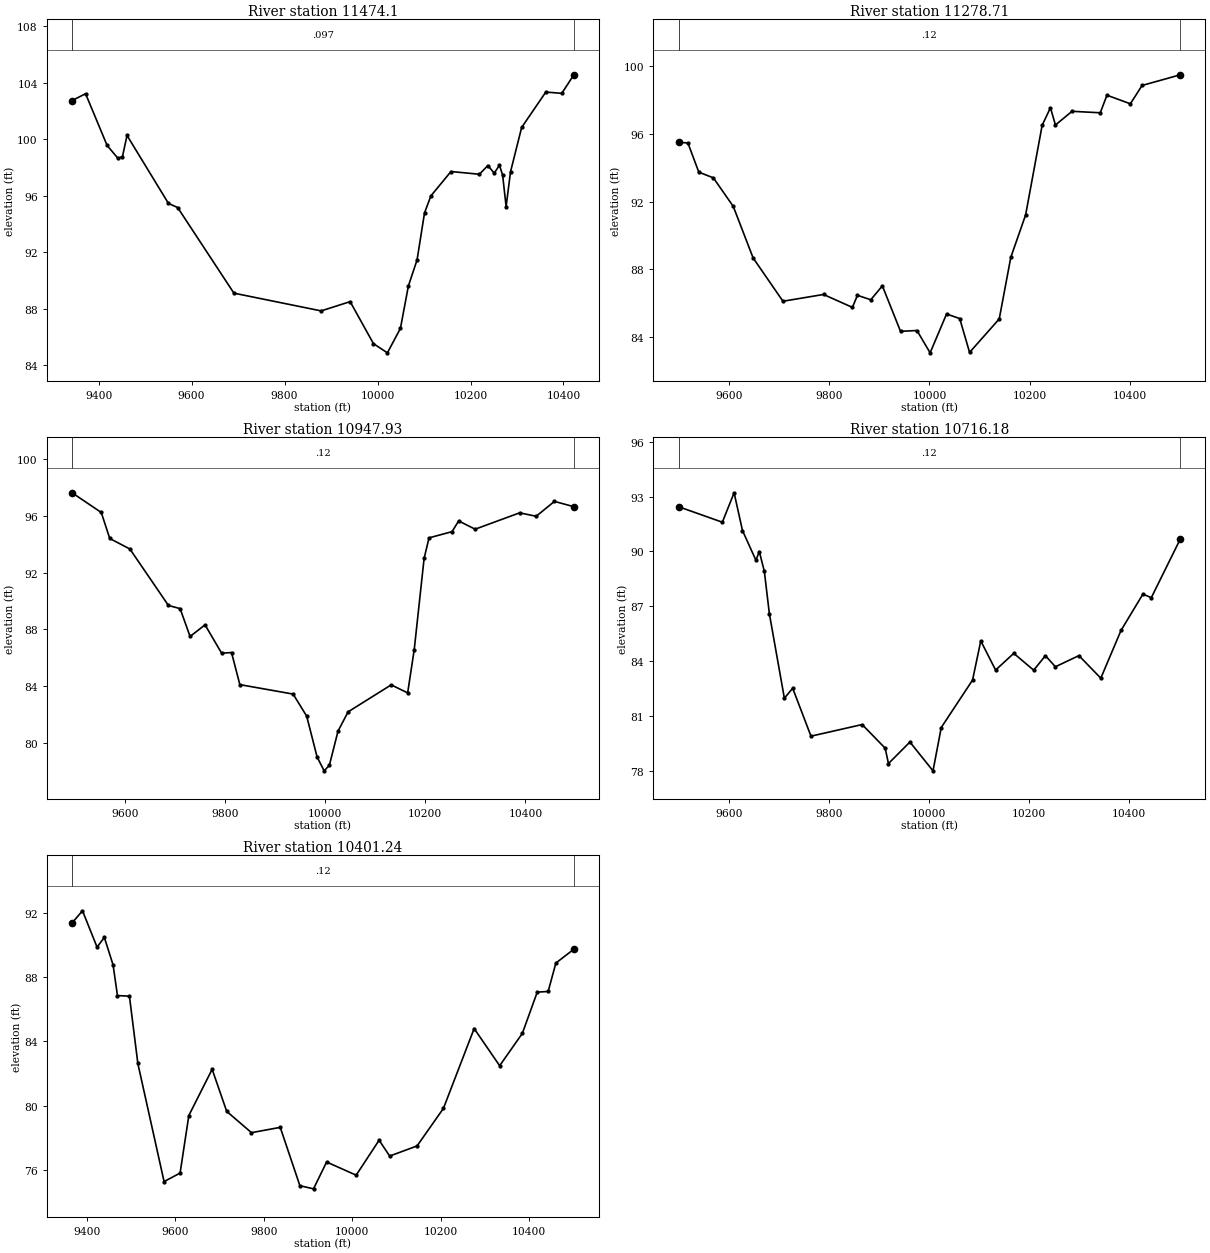
Type RM Length L Ch R = 1 , 11474.1,195.390400,195.390400,195.390400
XS GIS Cut Line= 4
1215985.38828734613618.3081145581215712.17071536 613648.34774287
1215294.47683561613880.0820185991215058.45118442614106.094460338
#Sta/Elev= 30
9342.991102.73789372.062103.2224 9418.2799.563539441.37598.655479451.27698.74978
9461.178100.26649550.29495.452169570.09895.158329691.13389.09208 9878.7387.83569
9941.12988.491559991.28885.51363 10021.384.8643610049.3386.6038410066.3389.59601
10085.0991.4525810101.07 94.774610114.6895.97896   1015897.7101410219.1697.51645
10237.3398.1364110250.9697.5962910262.36 98.154410269.1397.4452410276.5995.22976
10286.0897.6935310310.01100.833310361.98103.340310396.31103.248110422.31104.5644
#Mann= 3 , 0 , 0
9342.991   0.097       09342.991   0.097       010422.31   0.097       0
#XS Ineff= 2 , 0
       0                               0
Bank Sta=9342.991,10422.31
Exp/Cntr=0.3,0.1

Type RM Length L Ch R = 1 ,11278.71,330.773700,330.773700,330.773700
XS GIS Cut Line= 6
1215786.32504741613521.9254588931215604.20112438613605.582520712
1215465.47867388613649.3566341641215384.28627796613661.150883671
1215095.39267411613677.669808995 1214815.1596497613724.990839922
#Sta/Elev= 30
9499.08195.48689 9517.7495.45713 9539.5593.731939568.629 93.39619608.33191.71207
9648.02988.667999707.56986.11555 9788.5586.51484 9846.2685.751999856.26486.46412
9882.94286.20384 9906.06 87.02219942.296 84.3406 9975.1384.38779 10001.483.07111
10034.2285.3631910060.4885.0951710080.18 83.0968 10139.485.0712310162.4688.70398
 10192.191.2114510225.09 96.498810241.66 97.532910251.6196.5131110284.7597.32254
10341.1197.2348610354.4698.27135 10401.297.7655310424.5798.8470710500.9599.47729
#Mann= 3 , 0 , 0
9499.081    0.12       09499.081    0.12       010500.95    0.12       0
#XS Ineff= 2 , 0
       0                               0
Bank Sta=9499.081,10500.95
Exp/Cntr=0.3,0.1

Type RM Length L Ch R = 1 ,10947.93,231.751900,231.751900,231.751900
XS GIS Cut Line= 6
1215871.90369024613250.0020761641215701.87149917613289.028955083
1215448.55504843613326.4223558391215312.51650458613364.735385921
1215041.66014319613382.077369812 1214884.5543315613400.501302157
#Sta/Elev= 30
 9494.9497.626749553.24396.238349570.16294.405549610.39693.662789687.35289.68312
9710.61689.462599730.55787.496929760.40988.316839793.49786.32316 9813.3586.36295
9829.89484.104389936.29383.436949963.36681.882359984.16779.000929998.21678.02671
10008.6478.4163610025.9580.8275210046.0782.1858410132.1284.0863310164.9783.52114
 10178.186.5725410197.8193.0032610207.6694.4493410253.6494.8876810266.7895.64314
10299.67  95.05910388.5796.21334 10421.695.97023   1045897.01971 10496.896.64449
#Mann= 3 , 0 , 0
 9494.94    0.12       0 9494.94    0.12       0 10496.8    0.12       0
#XS Ineff= 2 , 0
       0                               0
Bank Sta=9494.94,10496.8
Exp/Cntr=0.3,0.1

Type RM Length L Ch R = 1 ,10716.18,314.944600,314.944600,314.944600
XS GIS Cut Line= 6
1215838.02429707613070.3461881061215663.79925811613110.119792563
 1215518.2534497613130.8631808521215263.82958169 613119.01971021
1215189.05890166613122.6859189431214850.10040026613191.823974147
#Sta/Elev= 30
9499.94392.447339587.406 91.59919610.88393.206899627.65391.140349654.48489.52211
9661.19289.999659671.25488.919279681.29486.601429711.23781.988939727.87282.53206
9764.38579.91438 9866.5680.54943 9912.51 79.25759919.09178.419439961.91679.59393
10008.0378.0211710024.4880.38697   1008782.97846 10103.485.1175110132.9983.52515
10169.2984.4378210209.0783.5169910232.4384.3106810252.44  83.70610299.3584.31337
10343.05 83.0813 10383.485.68802 10427.187.6727610443.9187.4784710501.83 90.6848
#Mann= 3 , 0 , 0
9499.943    0.12       09499.943    0.12       010501.83    0.12       0
#XS Ineff= 2 , 0
       0                               0
Bank Sta=9499.943,10501.83
Exp/Cntr=0.3,0.1

Type RM Length L Ch R = 1 ,10401.24,294.872200,294.872200,294.872200
XS GIS Cut Line= 6
1215881.55017352612792.6966980251215478.77239573612757.974475801
 1215334.6271459612800.344785006 1215216.9598798612892.138167719
1215127.56641461612946.4183547811214829.11246406613075.847518213
#Sta/Elev= 30
9366.607 91.38679390.17892.145629423.10889.880439439.57390.485179459.33188.77061
 9469.2186.860439496.27986.825769515.31282.628949574.58675.271329610.80975.80005
9630.56779.387469683.25582.268329716.18679.645359772.21678.317999837.18978.64966
9881.64475.014339912.421 74.81819942.03776.4900810008.8575.6692810060.7477.84898
10084.58 76.860810146.4677.4910210206.0979.8309410275.5784.8057710333.2282.49107
10384.5384.5065610418.2187.0768610442.8587.1181210460.33 88.888610500.97 89.7503
#Mann= 3 , 0 , 0
9366.607    0.12       09366.607    0.12       010500.97    0.12       0
#XS Ineff= 2 , 0
       0                               0
Bank Sta=9366.607,10500.97
Exp/Cntr=0.3,0.1