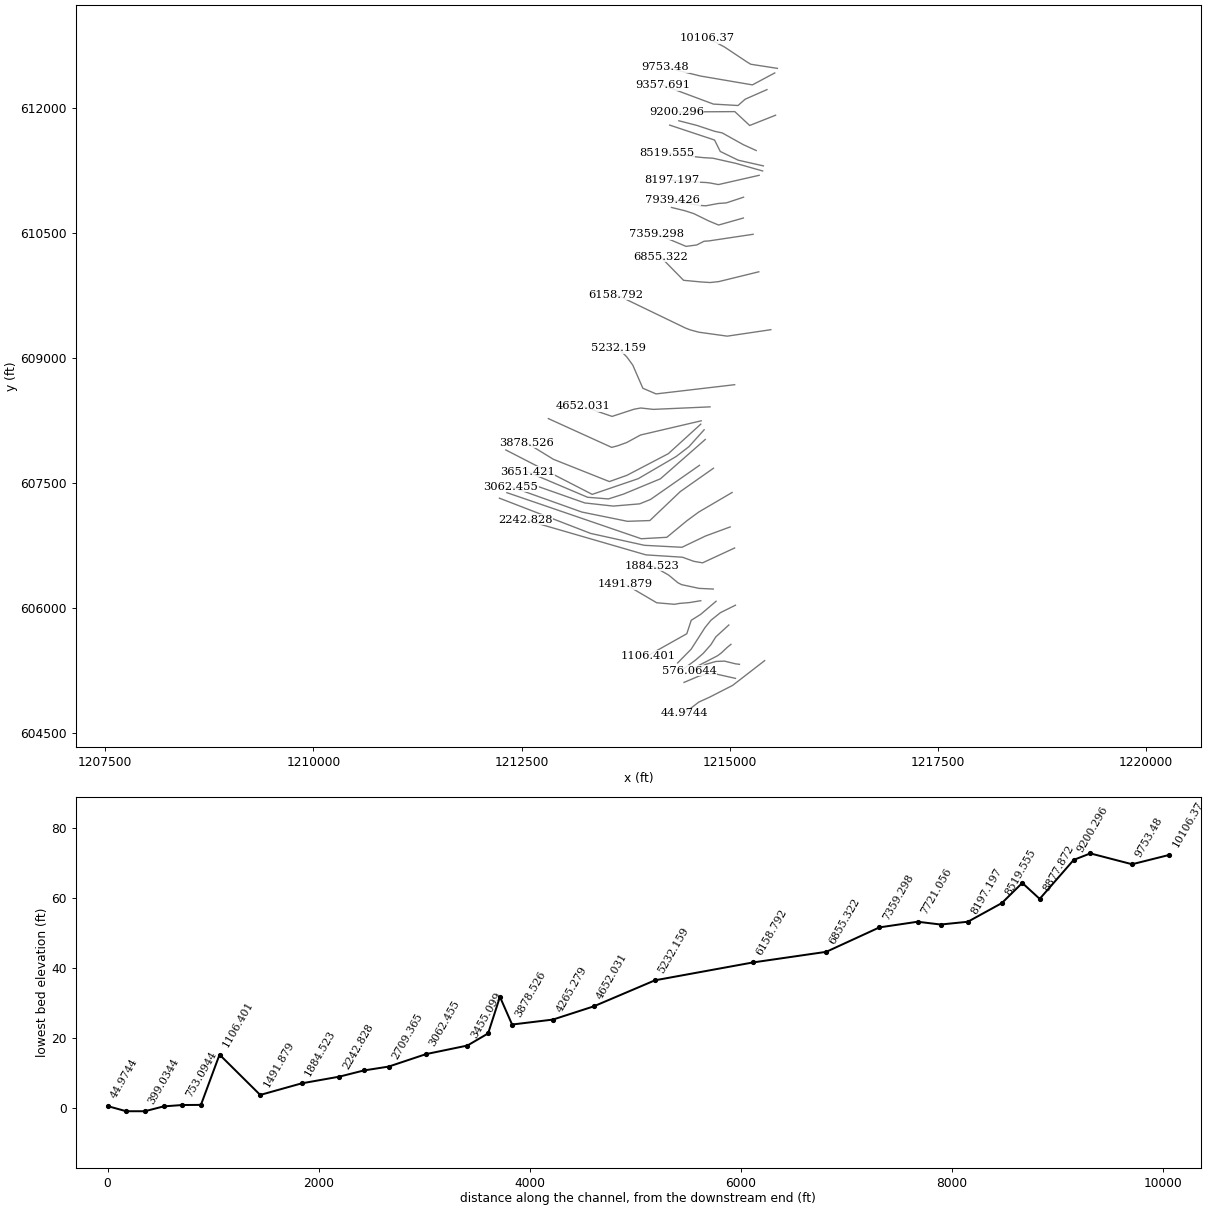
HEC-RAS study 76_ras.prj: 76

--- 76_ras.g01 (geometry) --- (continued)

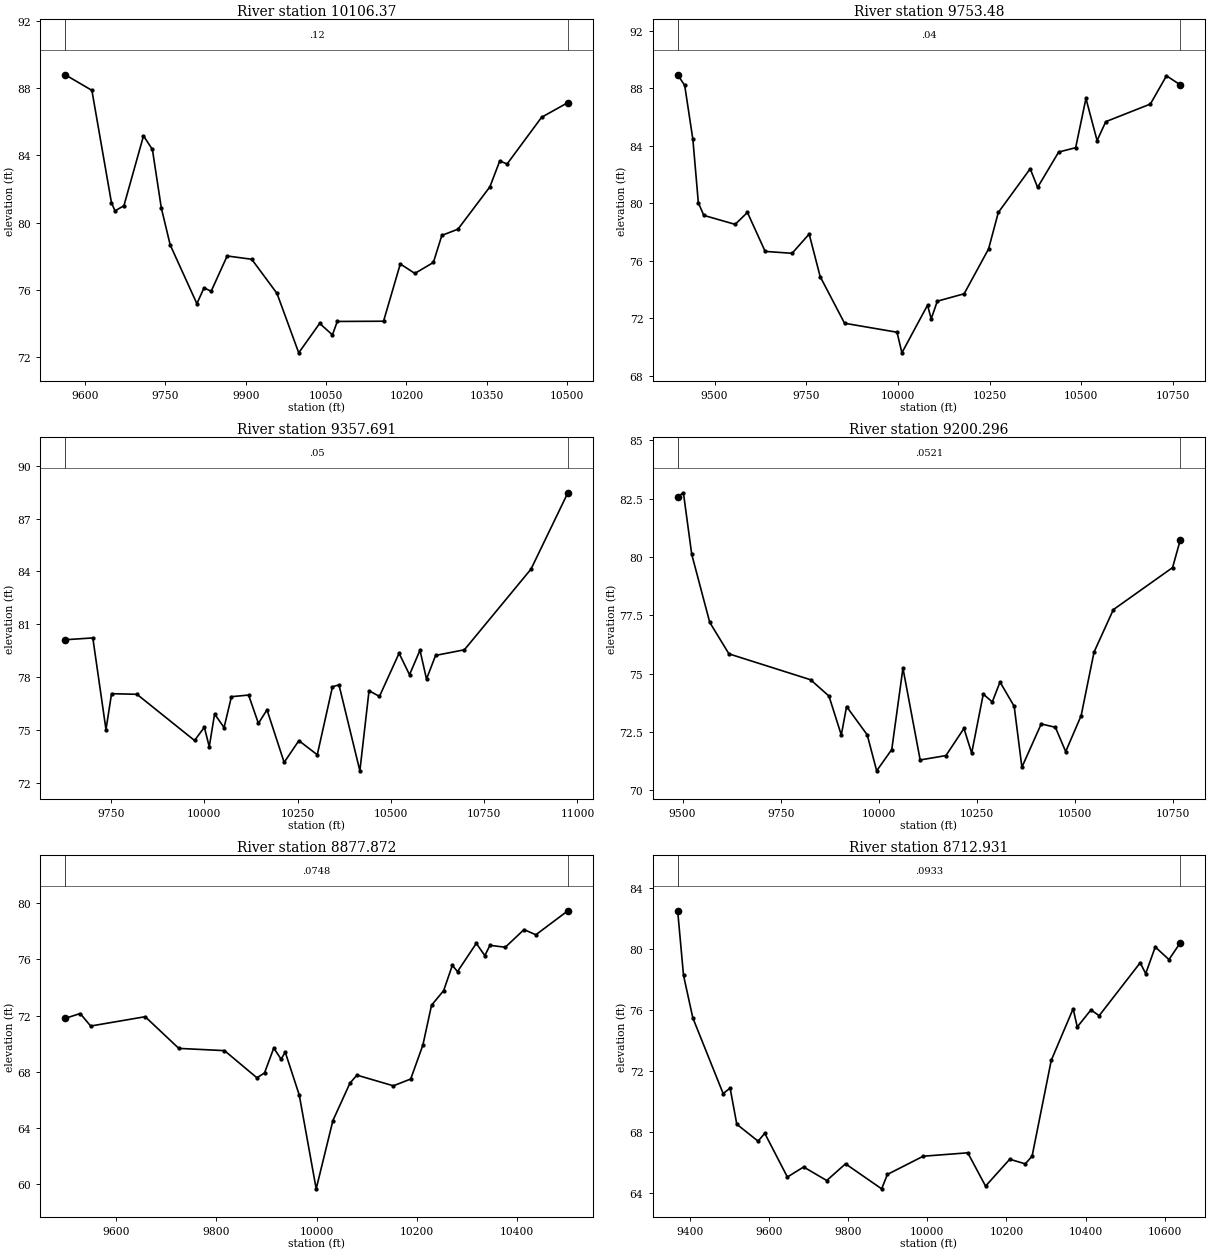
Type RM Length L Ch R = 1 ,10106.37,352.885700,352.885700,352.885700
XS GIS Cut Line= 6
1215572.52239579612480.1966980251215252.36272226612529.754158911
1215205.84961263 612557.736150751214937.78233997612736.474590182
1214828.08684867612795.0260940741214725.31858742612840.907297623
#Sta/Elev= 30
9563.53488.78324 9613.2287.857669649.73981.179099656.37980.696699672.97981.00173
9709.49785.152879726.09784.346969742.69780.872579759.29678.670919809.09575.18014
9822.37476.123959835.65475.917029865.53378.015479911.37677.819779958.48175.79002
    999972.2593710038.0774.0090210061.8973.3254510070.8974.1244210157.1974.13841
10188.4377.5421210215.5776.9790210250.1377.6309810265.9179.2380910295.96 79.6074
10355.5582.1247310373.9383.6618510387.6583.4834210451.9586.2568410500.9687.12955
#Mann= 3 , 0 , 0
9563.534    0.12       09563.534    0.12       010500.96    0.12       0
#XS Ineff= 2 , 0
       0                               0
Bank Sta=9563.534,10500.96
Exp/Cntr=0.3,0.1

Type RM Length L Ch R = 1 , 9753.48,395.788900,395.788900,395.788900
XS GIS Cut Line= 4
1215540.39236248612425.2007221431215272.00227299612282.015191168
1214648.91128466612388.1828091141214227.03628466612492.349475786
#Sta/Elev= 30
9399.36688.940859418.60188.199839440.91284.437679455.78680.03601 9470.66 79.1555
9556.18778.529719589.65379.360129637.99476.648469711.44176.515279758.03477.85603
9787.987 74.8969 9854.5571.648569997.65971.0218310010.9769.5882810080.86 72.9063
10090.8571.9521610107.4973.1829810180.7173.6989710247.2776.8151510273.8979.35724
10360.8182.3987310381.0881.1065910438.5383.5641110484.8383.8655610512.8887.29197
10543.2984.3614410566.95 85.6776 10688.686.9033510732.5488.8699810770.1888.23953
#Mann= 3 , 0 , 0
9399.366    0.04       09399.366    0.04       010770.18    0.04       0
#XS Ineff= 2 , 0
       0                               0
Bank Sta=9399.366,10770.18
Exp/Cntr=0.3,0.1

Type RM Length L Ch R = 1 ,9357.691,157.394400,157.394400,157.394400
XS GIS Cut Line= 5
1215446.70133808612225.2333117721215184.61593643612109.655126303
1215099.33177099612034.2459694741214803.97924009612051.302802578
1214194.05017352612278.807809129
#Sta/Elev= 30
9627.30780.123399701.22980.226749736.51775.026399751.429 77.06279819.55777.02799
9973.88474.4070410000.1675.15908 10013.374.0502710027.5975.9103710053.0175.14201
10072.7376.8933410118.7476.9849410145.0375.3777810168.0476.1457910214.0473.16493
10253.4874.3996510302.7773.5966310343.4477.4503310360.9577.5659110416.9772.68544
10441.4977.22866 10469.576.9091810522.0279.3550610550.0478.1383910578.0579.52726
10595.5677.8918810619.9279.23552 10697.1 79.552910875.6984.1329410974.4188.46128
#Mann= 3 , 0 , 0
9627.307    0.05       09627.307    0.05       010974.41    0.05       0
#XS Ineff= 2 , 0
       0                               0
Bank Sta=9627.307,10974.41
Exp/Cntr=0.3,0.1

Type RM Length L Ch R = 1 ,9200.296,322.424200,322.424200,322.424200
XS GIS Cut Line= 4
1215550.18097699611917.5911419691215239.18906245611794.432809129
1215060.75025231611960.9407204241214358.76675573 611956.74559994
#Sta/Elev= 30
9487.58682.593359502.25382.756449523.42580.119319569.29977.200829618.23275.84904
9826.293 74.73889873.079 74.03899904.49172.369229917.95373.58992 9970.5672.37558
9994.60470.8330810033.0871.7477510061.5575.2351210105.4371.2998110171.0571.48726
10216.9872.6510710236.6771.59236 10266.274.1231910289.1673.7870910308.8574.64025
10344.9473.6013310364.6270.9898210413.8472.8445610449.93    72.710476.1771.65793
10515.5573.1982110548.3575.9235210597.5777.7447410748.4979.5485210768.1380.73494
#Mann= 3 , 0 , 0
9487.586  0.0521       09487.586  0.0521       010768.13  0.0521       0
#XS Ineff= 2 , 0
       0                               0
Bank Sta=9487.586,10768.13
Exp/Cntr=0.3,0.1

Type RM Length L Ch R = 1 ,8877.872,164.941100,164.941100,164.941100
XS GIS Cut Line= 6
1215317.46341174611493.6876448141215161.83726176611564.530623118
1214910.09935775611704.9437271011214818.40157131611724.517638204
1214606.67492491611794.8806841621214388.52860701611851.213057309
#Sta/Elev= 30
9499.10671.804039528.88972.148329549.79571.258759658.43871.921429725.45969.66963
9816.54169.510259881.21867.579339896.36667.928389914.70869.690159929.38168.90318
9937.633 69.40389965.58766.348899999.303 59.687410032.6364.54226 10066.767.20767
10080.5367.7687610153.1367.0098110187.71 67.493810211.91 69.899410229.1972.73501
10253.3973.7784110270.6875.5723810280.9775.12678 10318.477.1344910335.4176.26252
10345.6276.9938610376.2576.8593310413.5178.1121710437.1277.7443610500.9479.45006
#Mann= 3 , 0 , 0
9499.106  0.0748       09499.106  0.0748       010500.94  0.0748       0
#XS Ineff= 2 , 0
       0                               0
Bank Sta=9499.106,10500.94
Exp/Cntr=0.3,0.1

Type RM Length L Ch R = 1 ,8712.931,193.376200,193.376200,193.376200
XS GIS Cut Line= 5
1215403.35175958 611309.298669861215101.30308378611377.818971306
1214885.95356494611482.6969837551214817.43326348611619.737586647
 1214279.0594663 611798.72939454
#Sta/Elev= 30
 9369.3782.498869384.18178.261729407.73175.466429484.24270.503839501.92870.85746
9518.74968.488949572.57667.377019589.39767.895479646.58965.023979687.62565.68304
9746.013 64.79499793.45365.890759884.68464.248659899.28165.19457 9989.78 66.3901
10102.3166.6134610147.2664.4269910208.3266.1911410247.5365.8883310264.81 66.3921
10313.2272.6839610368.5376.0705510378.9174.8726110413.4875.9934310434.2375.61284
10537.9579.0886510551.7878.3724510575.9880.1242610610.5579.2952810639.1980.39834
#Mann= 3 , 0 , 0
 9369.37  0.0933       0 9369.37  0.0933       010639.19  0.0933       0
#XS Ineff= 2 , 0
       0                               0
Bank Sta=9369.37,10639.19
Exp/Cntr=0.3,0.1

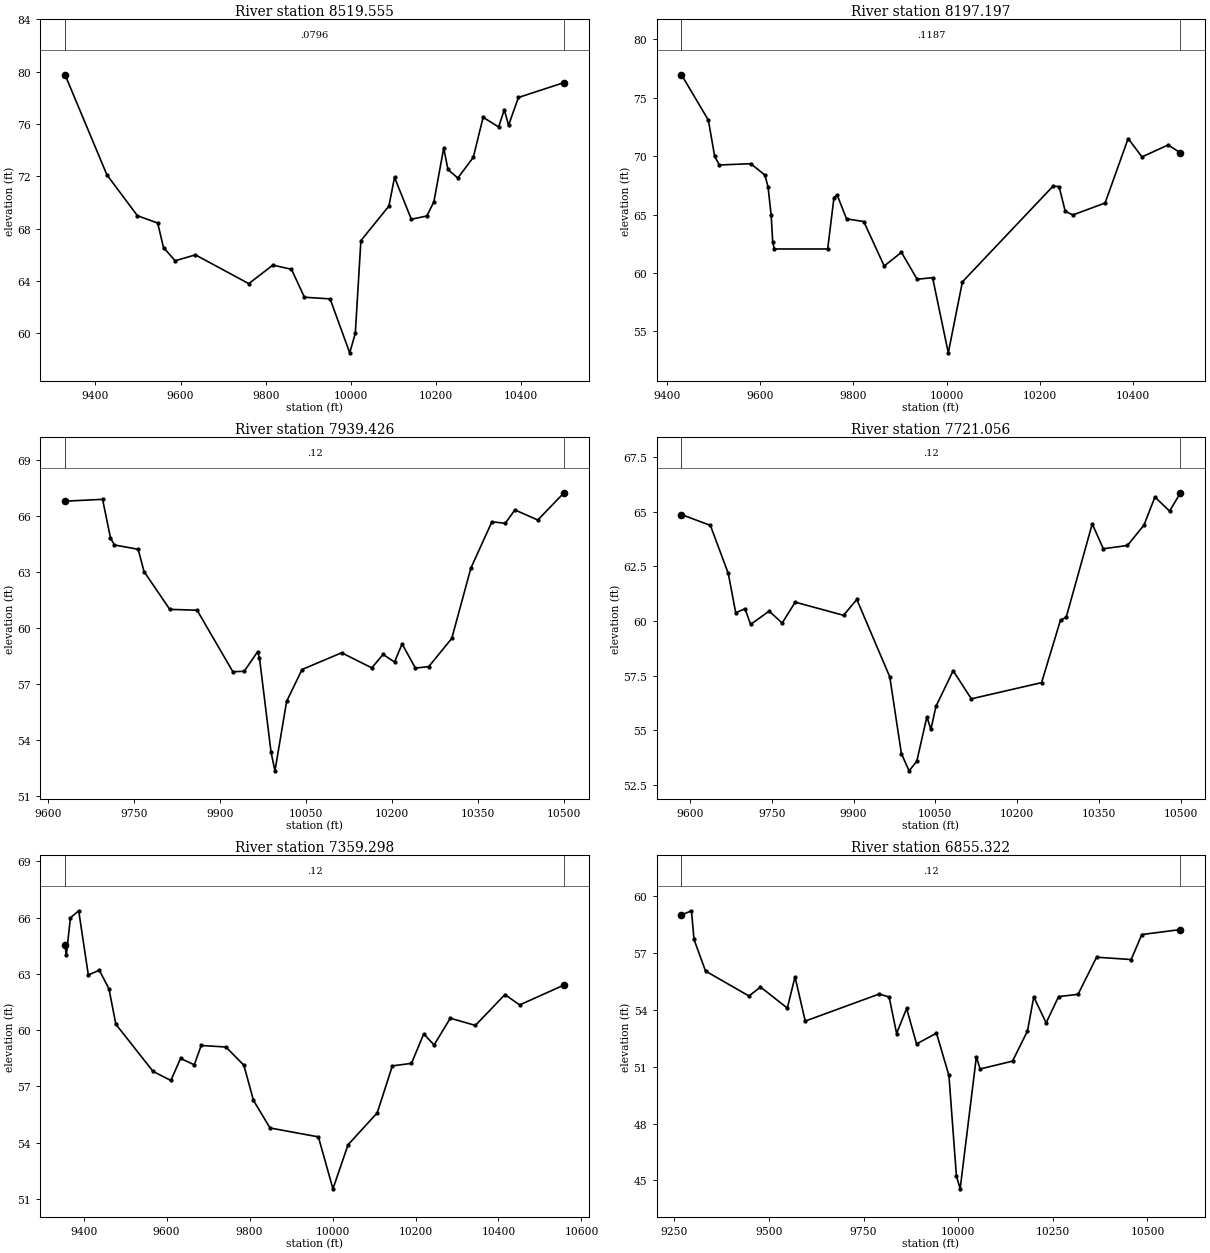
Type RM Length L Ch R = 1 ,8519.555,322.358300,322.358300,322.358300
XS GIS Cut Line= 6
1215394.91371208611248.2491112951215070.94537443611340.175671831
1214797.92497373611401.4426625221214686.05790347611408.094876304
1214589.48259977611417.9775813671214246.11508867 611465.60910961
#Sta/Elev= 30
9328.51179.763229426.83572.110899498.45268.987579546.197  68.4239559.83966.55026
9587.12265.540049634.86765.989489760.18663.790139816.86565.206899860.576 64.8859
9890.83862.74923 9951.25 62.62349997.36558.49706 10010.559.9878210023.63 67.0773
10089.4569.7223310102.6471.9169410142.2168.7101610178.5768.9651310195.1170.04123
10218.2674.1629510228.1972.5222110251.3471.8649610287.7373.4474810310.8976.51111
10347.3375.77195 10360.677.0988910370.5575.8943110393.7678.0269810500.9779.16599
#Mann= 3 , 0 , 0
9328.511  0.0796       09328.511  0.0796       010500.97  0.0796       0
#XS Ineff= 2 , 0
       0                               0
Bank Sta=9328.511,10500.97
Exp/Cntr=0.3,0.1

Type RM Length L Ch R = 1 ,8197.197,257.770300,257.770300,257.770300
XS GIS Cut Line= 6
1215353.24704537611196.1657779661214863.44638595611084.811329589
1214767.69267082611103.3358197361214719.55556496611109.359354662
1214471.81347787611121.3927960331214299.71568165611138.532398985
#Sta/Elev= 30
9431.67976.966929489.31773.083219502.77569.987289512.86969.24091 9580.1669.35119
9610.44168.37684 9617.1767.377779623.89964.937019627.26362.630279630.62862.04725
9745.02362.047259758.48166.44682 9765.2166.684299785.39764.627719822.40764.39678
9866.14760.589599903.15761.759429936.75959.455269969.88459.5898210003.5353.15202
10033.7959.2336210227.8967.4207110241.0367.3935110254.1765.2718810270.5964.96112
 10339.665.9860910389.0171.5072810418.6569.9358210474.7670.9540910501.1470.27796
#Mann= 3 , 0 , 0
9431.679  0.1187       09431.679  0.1187       010501.14  0.1187       0
#XS Ineff= 2 , 0
       0                               0
Bank Sta=9431.679,10501.14
Exp/Cntr=0.3,0.1

Type RM Length L Ch R = 1 ,7939.426,218.369900,218.369900,218.369900
XS GIS Cut Line= 6
1215165.74704537610933.1449446081214958.55538037610864.932284201
1214860.56343332610857.5408939011214712.45684739610829.966631076
1214622.94227449610835.8101970131214313.71937064610893.791289088
#Sta/Elev= 30
 9629.0266.77527 9694.5866.873029708.39764.815649715.30564.433079756.75464.20344
9767.116 63.00799812.01960.992159859.72560.947889922.229  57.6599942.05157.68274
 9965.4258.723679968.76458.387289989.03953.342689995.82252.3616710016.1756.07461
 10043.157.7765110112.3458.6730810164.9757.8651810184.7758.5835610204.6958.17916
10217.9959.1433510241.2557.8516110264.6357.9358410304.7359.4374910338.1463.19676
 10374.9 65.673710398.2965.59205   10415 66.3073 10455.165.7683610500.94 67.2236
#Mann= 3 , 0 , 0
 9629.02    0.12       0 9629.02    0.12       010500.94    0.12       0
#XS Ineff= 2 , 0
       0                               0
Bank Sta=9629.02,10500.94
Exp/Cntr=0.3,0.1

Type RM Length L Ch R = 1 ,7721.056,361.758700,361.758700,361.758700
XS GIS Cut Line= 6
1215163.14287874610683.1449446081214866.12718512610599.004968422
1214751.47211799610646.2654948731214569.71581083610735.297716315
 1214462.9701355610770.2014685791214299.90401887610810.016771826
#Sta/Elev= 30
9584.28764.866329637.27564.375849670.17362.175559683.81360.380159700.86360.56419
9711.09359.847879745.19260.455519769.061 59.91079792.93160.865889881.589 60.2645
9905.98960.987179966.42257.452639987.75253.94158 10001.953.1561410015.9953.59227
10034.4855.6230410041.8955.0505310051.0756.0982610082.69 57.730310116.0656.44699
10244.9357.1871110279.67 60.050510289.9960.1655110337.8864.4413210358.22 63.3057
10402.2963.4556510432.7164.3809110452.8965.67115 10479.8 65.023310499.7565.86415
#Mann= 3 , 0 , 0
9584.287    0.12       09584.287    0.12       010499.75    0.12       0
#XS Ineff= 2 , 0
       0                               0
Bank Sta=9584.287,10499.75
Exp/Cntr=0.3,0.1

Type RM Length L Ch R = 1 ,7359.298,503.975900,503.975900,503.975900
XS GIS Cut Line= 6
1215280.33037871610487.8324446081214746.60943666610407.932349578
1214691.40920565610404.2862409351214603.42019224 610359.56163156
1214475.29212841610342.764177069 1214125.5560801610489.257389739
#Sta/Elev= 30
9355.30764.527579358.31263.983239368.26465.987799388.16966.36186 9411.3962.94232
 9437.93   63.199461.15162.200579477.73860.316469567.308 57.80269610.43457.31677
9633.65658.49182 9666.8358.151049683.41759.18312 9743.1359.100059786.25658.13109
9809.47856.256139849.28654.785239965.92354.31069   1000151.54121 10037.453.88857
 10107.855.59478 10144.258.0949610190.2858.2286110219.8659.8011110244.7559.20772
10283.8860.6356110344.3560.2516910415.4961.8939710451.0661.3442210558.0262.40428
#Mann= 3 , 0 , 0
9355.307    0.12       09355.307    0.12       010558.02    0.12       0
#XS Ineff= 2 , 0
       0                               0
Bank Sta=9355.307,10558.02
Exp/Cntr=0.3,0.1

Type RM Length L Ch R = 1 ,6855.322,696.530200,696.530200,696.530200
XS GIS Cut Line= 6
1215348.91462332610037.4972023521214868.93096325609919.901205629
1214764.55727017609908.5415491411214653.54506724609915.685266353
 1214445.4748184609935.1933577511214165.75490108610219.890993208
#Sta/Elev= 30
9268.76558.992369295.14759.210839301.90357.699889332.30456.034659447.15154.71939
9477.55255.192759548.48754.082479568.75455.731619595.77753.397089791.032 54.8227
9817.43454.667439837.23552.742269863.63754.063649889.95452.195849942.55652.75853
9975.43250.539299995.22545.2372410005.1344.5565510047.9651.5090310057.8450.87247
 10143.551.2875510183.0352.8729810199.5954.6725110232.3653.3034810265.1354.68634
10316.6254.8081510365.5856.7634510457.0656.6423510485.1757.9585410587.2858.22065
#Mann= 3 , 0 , 0
9268.765    0.12       09268.765    0.12       010587.28    0.12       0
#XS Ineff= 2 , 0
       0                               0
Bank Sta=9268.765,10587.28
Exp/Cntr=0.3,0.1

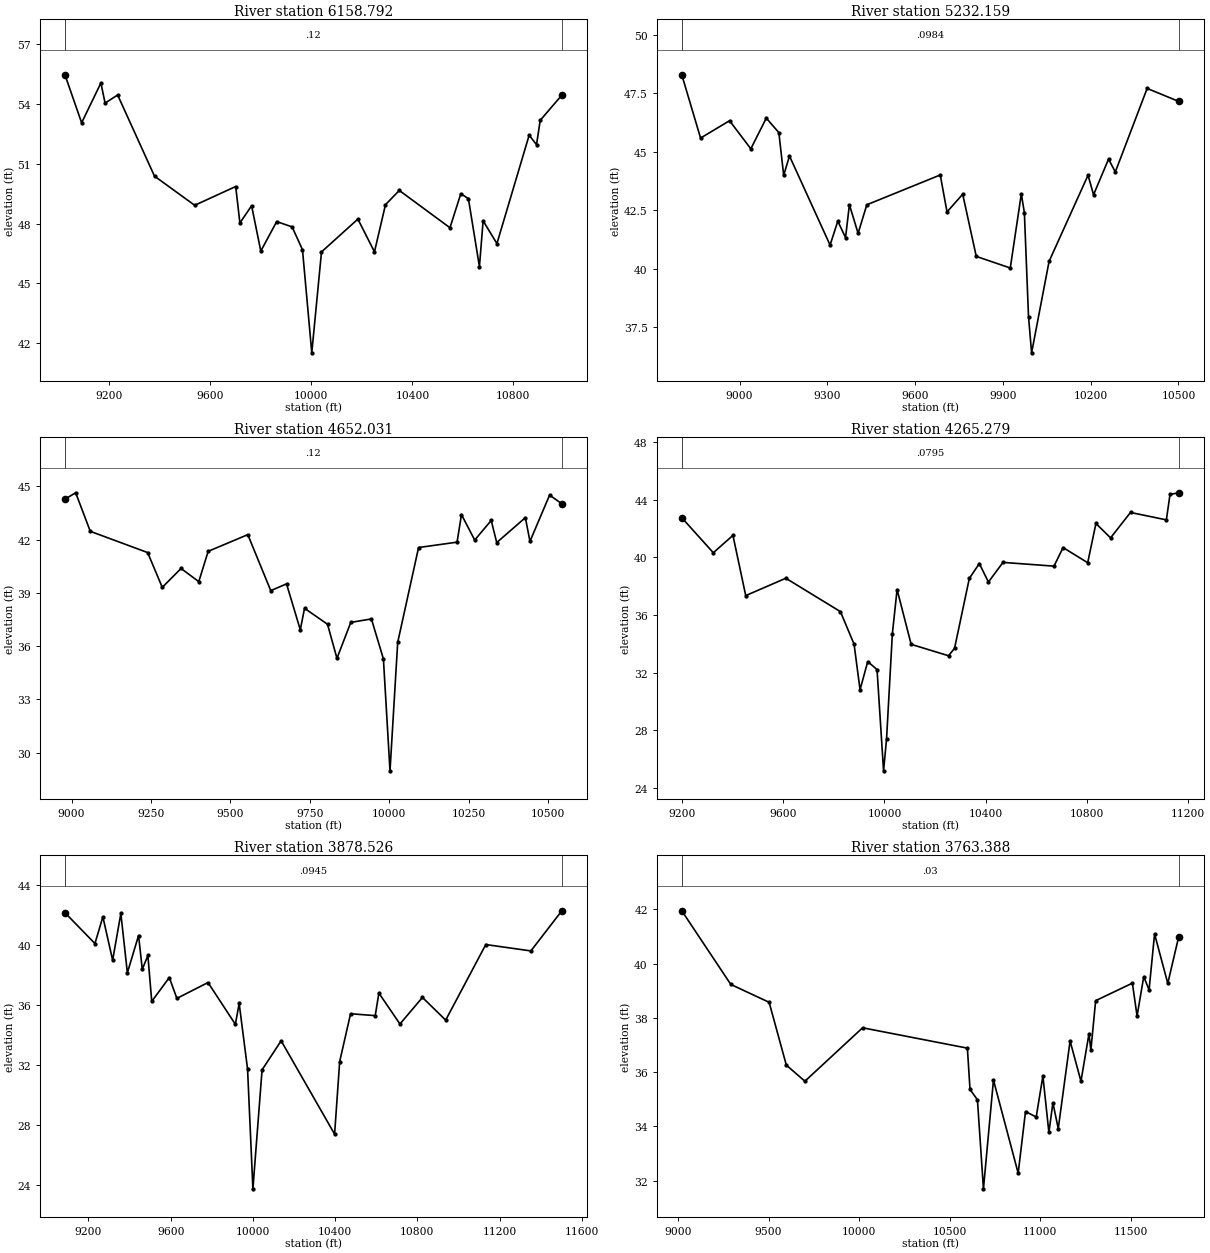
Type RM Length L Ch R = 1 ,6158.792,926.632000,926.632000,926.632000
XS GIS Cut Line= 6
1215493.61222508609342.1673337581214969.72753179 609264.72350955
1214629.21375418609312.0075900851214523.54594392609340.510054156
1214468.82440898609361.7103827451213635.37295666 609763.90651606
#Sta/Elev= 30
 9024.4755.475459090.51653.064039166.79555.062749183.37754.053049233.12454.46017
 9379.05  50.3859538.24148.921839700.56549.865289717.12648.031199763.49848.89979
9799.93446.622489862.86848.103989923.90847.837169964.976 46.688710001.7641.51317
10040.2346.5807810184.31 48.228610249.9246.58458 10293.648.95395 10348.349.66726
10548.8647.7939610591.82 49.502910621.8949.2556810665.5545.8417610680.1448.14192
10734.8346.9994710862.4652.4423410891.6451.9673810906.2253.1866410991.8454.45452
#Mann= 3 , 0 , 0
 9024.47    0.12       0 9024.47    0.12       010991.84    0.12       0
#XS Ineff= 2 , 0
       0                               0
Bank Sta=9024.47,10991.84
Exp/Cntr=0.3,0.1

Type RM Length L Ch R = 1 ,5232.159,580.128500,580.128500,580.128500
XS GIS Cut Line= 6
1215058.98880791608681.7411718051214115.25743848608571.102932304
1213956.56951073608638.9271860421213835.80014038608916.317571625
1213764.77458346609014.0583942531213658.20519996609121.719145238
#Sta/Elev= 30
 8802.5948.283798866.80945.582538965.90846.32294 9038.5845.123349091.43346.43492
9134.37645.815479150.89343.991129170.713 44.81749309.45141.014229335.87842.03532
9362.30441.333389375.51742.736419405.24741.514389434.97742.734649686.028 44.0071
9709.15142.429149762.742 43.18579809.125 40.53149925.35940.036079963.12343.19856
 9973.5442.39601 9987.6937.962129998.21936.4147810057.9940.3195610191.1243.99487
   1021043.1632510261.2444.6843810284.3844.1362510393.1547.70126 10500.947.14822
#Mann= 3 , 0 , 0
 8802.59  0.0984       0 8802.59  0.0984       0 10500.9  0.0984       0
#XS Ineff= 2 , 0
       0                               0
Bank Sta=8802.59,10500.9
Exp/Cntr=0.3,0.1

Type RM Length L Ch R = 1 ,4652.031,386.752400,386.752400,386.752400
XS GIS Cut Line= 6
1214763.19364625608415.5285230581214081.92724997608385.343545869
1213931.57726839608401.9095804691213851.88676775608387.576367855
1213587.25037178608301.0222936721213236.26856798608420.955774367
#Sta/Elev= 30
8979.04444.277019012.81144.636679058.78842.465399239.41141.268449285.38839.30839
9344.50140.373069400.329 39.63089429.88641.33849 9554.6842.278429626.929 39.1238
9676.548 39.50459719.94936.917489733.20538.129349805.61637.229459835.29635.31033
9878.81737.333989943.75437.53122 9981.5535.27817 10002.328.9728410026.5236.20789
10092.2541.5521610213.4441.85564 10227.343.4078910268.9141.9735110320.9243.07799
10338.2541.83154 10428.443.2343210442.9441.9006510504.6744.5054410543.2444.01838
#Mann= 3 , 0 , 0
8979.044    0.12       08979.044    0.12       010543.24    0.12       0
#XS Ineff= 2 , 0
       0                               0
Bank Sta=8979.044,10543.24
Exp/Cntr=0.3,0.1

Type RM Length L Ch R = 1 ,4265.279,386.752400,386.752400,386.752400
XS GIS Cut Line= 6
1214657.14829436608248.0577448011213928.29402992608077.490580693
1213763.92637527607987.8097060471213657.77898958607949.494893596
1213582.32600564 607929.00923875 1212821.7925685608274.566378802
#Sta/Elev= 30
 9199.75 42.75369324.28440.324339401.78241.528039452.32437.351939610.68938.55598
9826.33636.239619880.24733.981219903.83430.820969934.15932.774079970.93132.22417
9996.66125.1969510008.6227.4379110031.4534.7030410050.1237.7723310105.6633.97136
10253.2833.1800710277.0833.6953810335.3638.53949 10374.939.5752510410.8638.29129
10468.4139.6554310669.8139.3946310705.7840.6833810802.9539.6332210835.4642.35435
10893.2641.3557910972.0243.1191711113.6242.6043311128.0744.3685911162.2444.48349
#Mann= 3 , 0 , 0
 9199.75  0.0795       0 9199.75  0.0795       011162.24  0.0795       0
#XS Ineff= 2 , 0
       0                               0
Bank Sta=9199.75,11162.24
Exp/Cntr=0.3,0.1

Type RM Length L Ch R = 1 ,3878.526,115.138400,115.138400,115.138400
XS GIS Cut Line= 6
1214652.15010116608208.0721993151214262.29103249607853.200482979
1213764.98853874607593.4359307741213554.34723708607518.431402937
1212882.13157332607786.046086162 1212557.2334199607985.315042987
#Sta/Elev= 30
9085.75342.172769231.64940.118019270.17941.897939317.72339.007349357.65142.12153
9389.38338.16673 9443.7840.652769461.91238.401599489.11139.323989507.89836.26367
9593.373 37.85289630.28136.464029781.51937.52081 9914.6134.739489933.17136.12664
9974.00531.749229999.99123.7774910044.54 31.702710137.3433.6388210397.3427.42173
10422.0632.2581810475.0235.4414310594.9135.3160510612.7436.8181610715.1534.75813
10824.6236.5279210937.6235.0169311132.7740.0507911352.1539.6267211502.62 42.3009
#Mann= 3 , 0 , 0
9085.753  0.0945       09085.753  0.0945       011502.62  0.0945       0
#XS Ineff= 2 , 0
       0                               0
Bank Sta=9085.753,11502.62
Exp/Cntr=0.3,0.1

Type RM Length L Ch R = 1 ,3763.388,111.966700,111.966700,111.966700
XS GIS Cut Line= 6
1214692.05381334 608139.967653171214511.02372903607938.539812893
1214355.49083969607818.7029964921213901.64076915607553.532168761
1213348.35163823607364.8529259561212310.49659279607898.184221685
#Sta/Elev= 30
9020.51741.94423 9291.3439.228679502.938 38.57039597.932 36.25379700.52635.66037
10019.1537.63044 10597.936.8800410612.3735.3568110653.3734.9780310686.5731.69308
 10741.9 35.702810878.3832.2704510918.9534.5442510977.9734.3409411014.8635.84909
11048.0533.7726411070.1934.86515 11099.733.9138611165.08 37.143611225.11 35.6607
11269.3837.4083111279.9336.8056811306.2638.6301711509.14 39.276611534.96 38.0655
11571.8539.5123211601.3639.0299411631.6641.0890311704.6439.2679711764.7740.98151
#Mann= 3 , 0 , 0
9020.517    0.03       09020.517    0.03       011764.77    0.03       0
#XS Ineff= 2 , 0
       0                               0
Bank Sta=9020.517,11764.77
Exp/Cntr=0.3,0.1

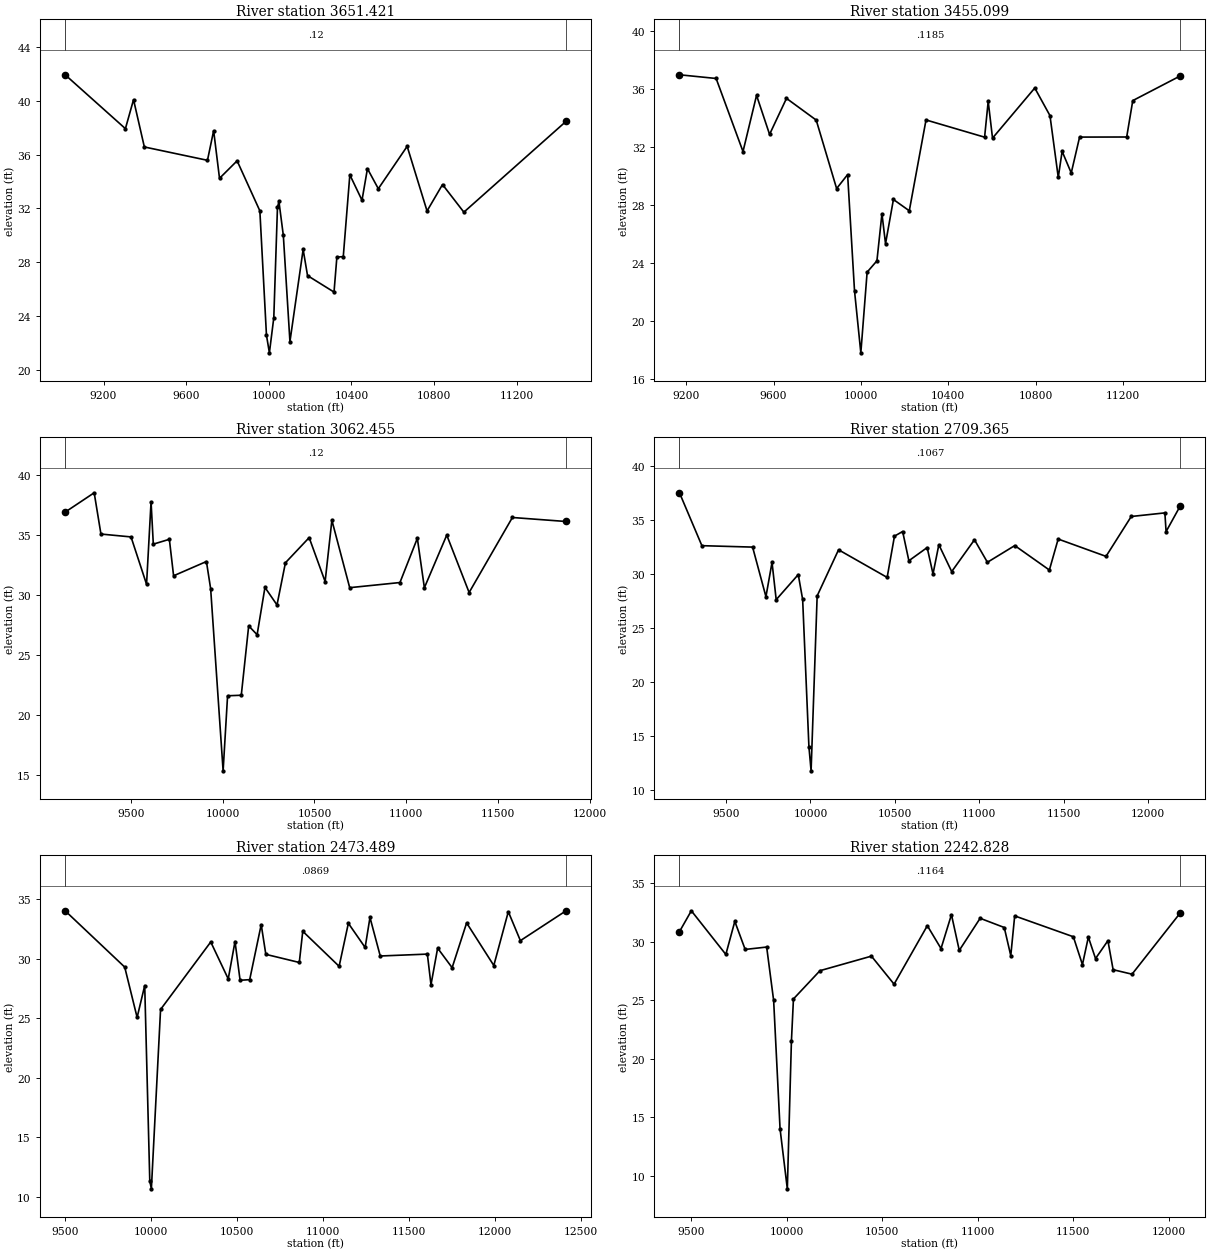
Type RM Length L Ch R = 1 ,3651.421,196.322100,196.322100,196.322100
XS GIS Cut Line= 6
1214705.96076095608023.991486311 1214167.7663165607551.769264102
1213723.32187209607367.7414863261213543.27899078607309.957040802
1213292.72398567607329.911023706  1212568.137472607637.672912166
#Sta/Elev= 30
 9014.07 41.95019305.79637.937579345.07940.095659397.455 36.57399702.98435.57931
9732.88937.786649761.29734.23858 9846.5235.54199  9956.631.815159988.55822.55956
10002.7621.2414310024.0723.8594810041.8232.0683910048.9232.5183410070.2329.98614
10102.1922.0797110166.1128.9378810187.4126.99369 10315.625.7671510329.3928.36676
 10360.428.4109510392.1634.4998910451.0432.6056710477.3734.9575110530.0333.46428
10669.6536.62043 10765.931.8059410840.75 33.775510944.1231.7175411438.7838.48163
#Mann= 3 , 0 , 0
 9014.07    0.12       0 9014.07    0.12       011438.78    0.12       0
#XS Ineff= 2 , 0
       0                               0
Bank Sta=9014.07,11438.78
Exp/Cntr=0.3,0.1

Type RM Length L Ch R = 1 ,3455.099,392.644100,392.644100,392.644100
XS GIS Cut Line= 6
1214636.66832787607713.7009837631214049.31785786607304.183752298
1213917.76590246607250.7466501441213600.47865725607224.125986367
1213259.27909726607261.8314275891212532.44139904 607517.83609581
#Sta/Elev= 30
9169.299  36.9899337.13436.733829460.17631.683829522.19935.568119581.856   32.87
9659.31435.358559795.39633.857749888.82729.127099939.22830.091189970.76722.06226
9999.69717.77347 10028.523.3502510073.3524.1309710096.3627.3849610112.77  25.315
10148.89 28.370210221.57 27.590310298.1633.8668310566.3632.6769610582.8635.15515
10602.6732.6113610796.1236.0754510865.6934.1666410903.6629.8999110921.3431.69785
10963.0830.2051311001.3432.68304   1121732.6889811244.8335.2041911462.7636.91398
#Mann= 3 , 0 , 0
9169.299  0.1185       09169.299  0.1185       011462.76  0.1185       0
#XS Ineff= 2 , 0
       0                               0
Bank Sta=9169.299,11462.76
Exp/Cntr=0.3,0.1

Type RM Length L Ch R = 1 ,3062.455,353.089800,353.089800,353.089800
XS GIS Cut Line= 6
1214804.22245532607678.4264306281214405.67009261607398.025667578
1214040.48977101607050.2941480431213771.77706113 607041.10738875
1213224.27003917 607152.333777011212371.80907071607456.642827854
#Sta/Elev= 30
9141.64636.930319299.87138.546689336.70535.099149500.627 34.85979585.22730.90375
9609.78537.796839622.06434.255999709.52134.66026  9732.631.613719911.48532.80522
9934.53230.5332110002.4515.3221810026.7821.5914610101.4421.63571 10141.827.42965
10187.7626.6918310230.4430.6429610296.0929.1778810342.0532.7012810471.3234.80066
10558.3631.1294910595.1936.2486410692.2830.6208110966.0731.0501211060.8934.74193
11099.2130.6144911221.1435.0117811343.0630.2175511578.8336.4822811871.2236.14825
#Mann= 3 , 0 , 0
9141.646    0.12       09141.646    0.12       011871.22    0.12       0
#XS Ineff= 2 , 0
       0                               0
Bank Sta=9141.646,11871.22
Exp/Cntr=0.3,0.1

Type RM Length L Ch R = 1 ,2709.365,235.876300,235.876300,235.876300
XS GIS Cut Line= 6
1215028.21586782607387.4113671631214627.77324015607152.696966544
 1214484.9963491607047.7805828011214244.54960009 606849.23519884
1213937.33684209606831.961550996 1212323.3644003607385.250681952
#Sta/Elev= 30
9224.26837.553029357.06432.647149657.54632.514479736.56327.916229772.61231.09571
9797.30127.638539928.07729.965479954.05927.659619991.18314.0113910004.0711.76236
   1004027.9871710166.77 32.265110454.7429.7016410498.0833.5311810546.5133.96124
 10583.431.2488510691.8232.4719410726.4130.0264310761.0132.7371110837.12 30.2422
10972.0433.1936811048.7631.1061211210.8532.6555611415.8430.3881611467.9633.26076
11751.4431.6546811900.9335.3542412100.2635.6879312107.2733.9506112191.9736.35571
#Mann= 3 , 0 , 0
9224.268  0.1067       09224.268  0.1067       012191.97  0.1067       0
#XS Ineff= 2 , 0
       0                               0
Bank Sta=9224.268,12191.97
Exp/Cntr=0.3,0.1

Type RM Length L Ch R = 1 ,2473.489,230.661200,230.661200,230.661200
XS GIS Cut Line= 6
1215004.72666213606973.7609493581214708.94437116606864.764175519
1214426.00948647606729.3128861341213975.85752338606753.036729857
1213330.50360176 606895.704538421212234.12421787607318.957975015
#Sta/Elev= 30
9499.03934.03334 9845.8429.29829    9918 25.06579962.25527.746349991.75911.31779
   1000110.6509610054.5325.7339410346.6731.4111910448.52 28.305910487.9431.45003
10517.5128.1913610573.3628.2412910640.4432.8708110667.3230.37029 10862.2 29.6874
10882.3632.3101811094.04 29.3632 11147.832.98179 11245.530.9464511273.6333.47317
11333.4230.2317711607.7330.3909211628.8327.8129611667.5130.8925211751.9229.24956
11836.3233.0150411994.5829.4318312078.9833.9575812149.3231.5226612415.1234.03415
#Mann= 3 , 0 , 0
9499.039  0.0869       09499.039  0.0869       012415.12  0.0869       0
#XS Ineff= 2 , 0
       0                               0
Bank Sta=9499.039,12415.12
Exp/Cntr=0.3,0.1

Type RM Length L Ch R = 1 ,2242.828,358.305000,358.305000,358.305000
XS GIS Cut Line= 6
1215058.19923794606720.722312704 1214673.4232159606542.552238166
1214568.84194559606560.6880497191214431.97021887606610.077586576
1213993.43067104606638.1828691811212543.93633333607058.259253672
#Sta/Elev= 30
9436.97930.856699499.16632.638469679.94128.908599726.94231.732339781.17529.33648
9893.85429.540779930.42524.976359964.01914.01186 10002.18.891684 10023.5 21.4877
10034.1725.1085810173.1827.5225910442.76 28.764310561.4526.3703710735.6631.36559
10807.3929.4116510862.05 32.308110903.0429.2549711012.3431.9969411138.7331.21019
11172.8928.8068511193.3832.2018711500.8130.4192211548.3928.0377811579.3730.38994
11616.9528.5579511681.8530.0834411709.1727.6061711808.23 27.222912061.5132.46738
#Mann= 3 , 0 , 0
9436.979  0.1164       09436.979  0.1164       012061.51  0.1164       0
#XS Ineff= 2 , 0
       0                               0
Bank Sta=9436.979,12061.51
Exp/Cntr=0.3,0.1

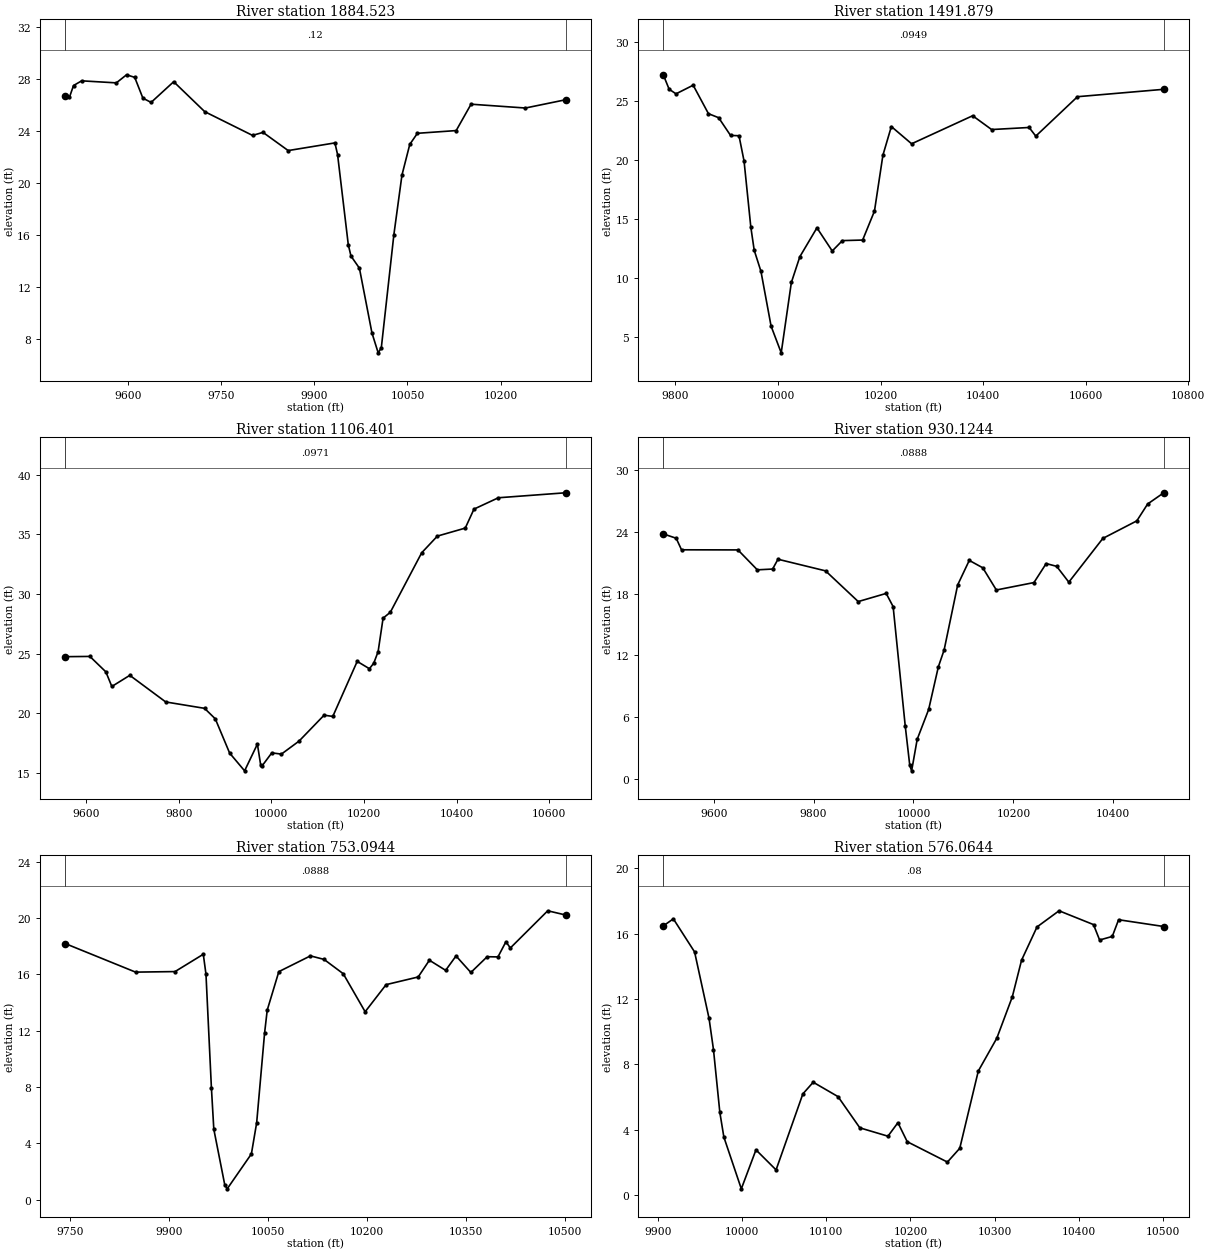
Type RM Length L Ch R = 1 ,1884.523,392.644100,392.644100,392.644100
XS GIS Cut Line= 6
1214802.02596478606227.8413907351214633.05816464606235.725581673
1214422.90832518606280.3633514141214378.04614254606302.804880386
1214266.23199181606395.6792034851214070.42892501606507.309702188
#Sta/Elev= 30
9499.138 26.69449506.08826.60618 9512.6527.506499525.77327.867289581.56727.71069
    959828.332539611.14728.133369624.30126.536499637.50426.209489673.85927.79909
9723.81725.499189800.78823.674319817.60923.907889858.13522.509379933.34223.09847
9937.609 22.20749954.882 15.2724  9959.214.406469972.76713.47446 9992.958.499787
10002.986.96984310008.037.36168710028.2516.0530110041.2520.6263110053.8322.98384
10066.1123.8365410128.5124.0457910152.45 26.072110239.9625.7787410304.6226.41323
#Mann= 3 , 0 , 0
9499.138    0.12       09499.138    0.12       010304.62    0.12       0
#XS Ineff= 2 , 0
       0                               0
Bank Sta=9499.138,10304.62
Exp/Cntr=0.3,0.1

Type RM Length L Ch R = 1 ,1491.879,385.477800,385.477800,385.477800
XS GIS Cut Line= 6
1214652.07856432606087.9933943391214517.61131427606065.619389414
1214396.39687106606055.2772747041214335.97828408606044.773262572
1214122.93363613606063.0390696971213741.26477456606287.193797916
#Sta/Elev= 30
9776.43827.199579787.87125.978369801.26625.585499834.71526.316589864.53523.90652
9884.41623.564489907.60922.065169924.10422.038659933.98119.88974 9947.1514.30119
9953.73512.347649966.90510.554959986.6595.91870610006.413.65651810026.189.612542
10042.7511.7964710076.0514.24027 10105.9  12.28110125.6613.1585710165.1713.20579
10188.2215.6574310204.6920.3892310221.1522.8160210260.6721.3573510379.6623.73113
10416.6622.5623310489.7922.7378210502.75 22.005910584.0725.3431110752.2525.96937
#Mann= 3 , 0 , 0
9776.438  0.0949       09776.438  0.0949       010752.25  0.0949       0
#XS Ineff= 2 , 0
       0                               0
Bank Sta=9776.438,10752.25
Exp/Cntr=0.3,0.1

Type RM Length L Ch R = 1 ,1106.401,176.276300,176.276300,176.276300
XS GIS Cut Line= 5
1214835.78606007606081.2137773931214651.17736441605924.106103033
1214537.42170823605852.9464098071214484.06273976605691.045266077
1214018.92039379605429.833552733
#Sta/Elev= 30
9554.68924.744479608.14624.765759642.61123.473889655.53522.247769694.30823.18221
9771.85320.952129855.68920.417729878.90819.537489909.867 16.66969942.17715.18139
9969.81217.422369976.72115.711819980.17515.61023 10000.9 16.686610021.6316.58304
10059.6317.66916 10113.819.8445610132.6119.7401510185.2924.3499210211.6323.73706
10221.0624.2026610230.4425.1667110241.1627.9714410256.7828.4640810324.5133.44837
10358.3834.8463210418.5835.51674 10437.437.1069310490.0838.0578110635.2238.47521
#Mann= 3 , 0 , 0
9554.689  0.0971       09554.689  0.0971       010635.22  0.0971       0
#XS Ineff= 2 , 0
       0                               0
Bank Sta=9554.689,10635.22
Exp/Cntr=0.3,0.1

Type RM Length L Ch R = 1 ,930.1244,177.030000,177.030000,177.030000
XS GIS Cut Line= 6
1215068.21955424606033.6843686091214887.68842589605944.015052888
1214774.64263289605853.4798289131214703.50823866605766.246157279
1214535.85761607605504.8364464891214373.70656599 605340.30905843
#Sta/Elev= 30
9499.10323.782139524.95523.361519535.64622.240739648.603 22.22959687.39420.29819
9717.98820.37518 9728.7321.325259823.92120.199719889.39117.221969945.34918.01287
9959.26816.730149983.4135.1924359992.5581.3399299996.2660.813834 10007.43.868271
10030.366.76181610049.7210.8890410061.33 12.532710088.43 18.833710111.66 21.2128
10138.7520.4930910165.8518.3449710241.15 19.064410265.61 20.906710286.6320.63722
10310.9519.1038410379.0723.3442710447.0625.0453710468.7326.6811710500.9527.76808
#Mann= 3 , 0 , 0
9499.103  0.0888       09499.103  0.0888       010500.95  0.0888       0
#XS Ineff= 2 , 0
       0                               0
Bank Sta=9499.103,10500.95
Exp/Cntr=0.3,0.1

Type RM Length L Ch R = 1 ,753.0944,177.030000,177.030000,177.030000
XS GIS Cut Line= 6
1214988.92065484 605796.192385861214832.53168144605653.334204521
1214773.13961488605559.1366061241214680.79707187605454.626293689
1214587.39239705605373.2811571091214449.00707547605272.468235693
#Sta/Elev= 30
9742.28718.182079849.06616.153379908.89316.191429951.72517.420819955.78616.00426
9964.0057.9563399967.6675.0072019984.2691.0608829987.9490.77810210024.633.254432
10032.635.46753210044.6311.8292410048.6313.4572910066.2216.1875310114.1417.30578
10134.7217.0561210163.8616.0398910197.0513.3410210228.8415.2652810277.4615.80885
10294.4416.9966410319.0816.2798810334.8317.3002510357.29  16.12810382.0317.24606
10398.3817.2324110410.4518.3076810417.1617.8656910473.84 20.505210500.9120.20624
#Mann= 3 , 0 , 0
9742.287  0.0888       09742.287  0.0888       010500.91  0.0888       0
#XS Ineff= 2 , 0
       0                               0
Bank Sta=9742.287,10500.91
Exp/Cntr=0.3,0.1

Type RM Length L Ch R = 1 ,576.0644,177.030000,177.030000,177.030000
XS GIS Cut Line= 6
1215014.39117635605563.9974527281214968.20699237605526.285015229
1214899.65088562605461.3796885151214854.66506827605427.611891832
1214617.34634144 605304.461149421214515.32746467605247.406753709
#Sta/Elev= 30
 9906.2616.466529918.24816.898769943.47614.874669960.63810.814929965.9178.900233
9973.4895.0546299978.257 3.55002    99990.38299310016.412.76768510040.291.541719
10072.126.19106710084.426.90441210113.916.02353910139.814.11469110173.223.602682
10185.064.42969510196.133.26618810243.862.02021510258.552.86334810280.587.590348
 10302.69.60095710320.9612.1255910331.9814.3703610350.33 16.403310376.5217.39218
10417.4516.5470210424.7115.6035710439.7515.8225610447.2616.84421 10500.916.42988
#Mann= 3 , 0 , 0
 9906.26    0.08       0 9906.26    0.08       0 10500.9    0.08       0
#XS Ineff= 2 , 0
       0                10375.73       0
Bank Sta=9906.26,10500.9
Exp/Cntr=0.3,0.1

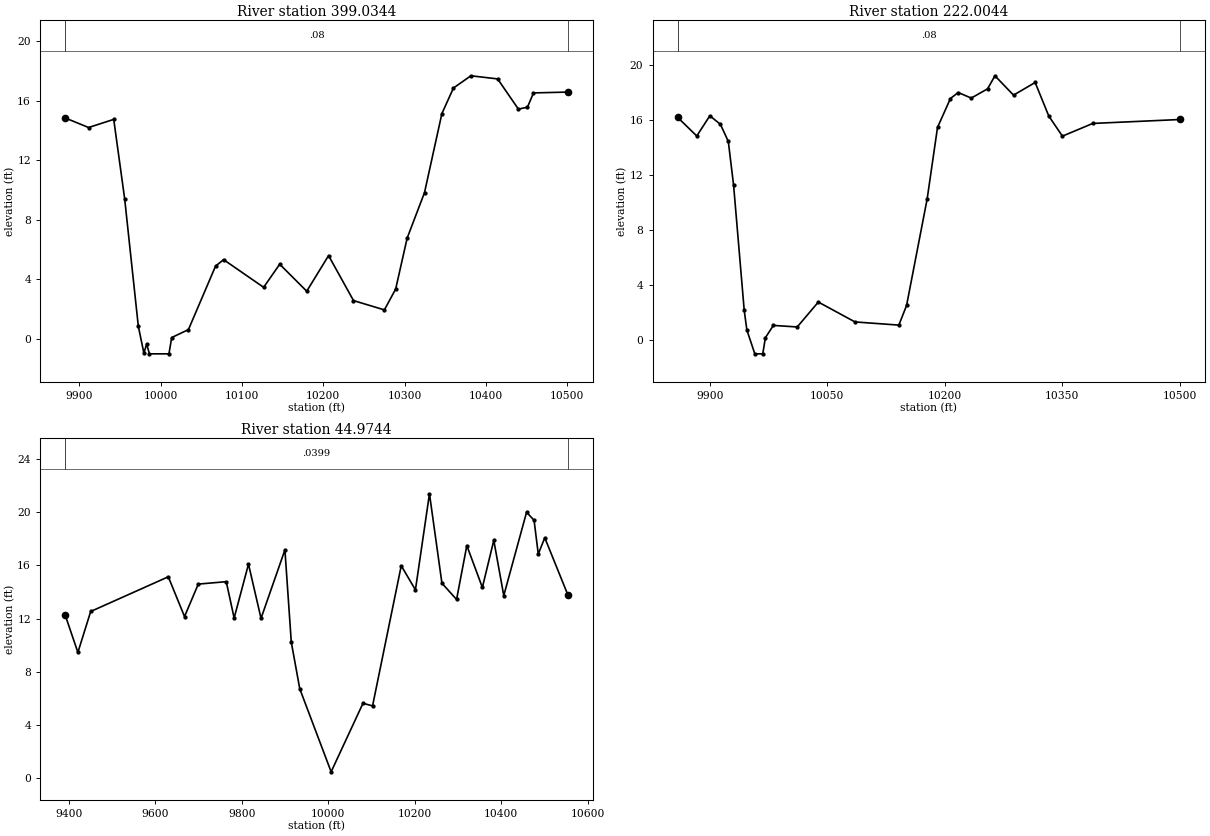
Type RM Length L Ch R = 1 ,399.0344,177.030000,177.030000,177.030000
XS GIS Cut Line= 6
1215116.55155689605323.8835351591215067.59100718605330.108301038
1214937.48086365 605362.355905141214833.92100777605358.396062721
1214714.12813119605324.246099108 1214528.0776017605236.252152765
#Sta/Elev= 30
  9882.714.858219911.42314.216249942.34214.762929955.778 9.430849972.5850.857754
 9979.43-0.949359982.853-0.341989986.276  -0.99910010.25  -0.99910013.670.096837
10034.220.62987510067.574.89607610077.435.33440910126.733.47198810146.495.025942
10179.743.21049510206.595.60630410237.252.58119810275.251.95449110289.133.358658
10303.236.77751510324.599.83818310345.9615.15163 10360.216.8722210381.6717.69423
10414.5217.4841610440.0815.4543210451.2115.5802410458.6416.5423810500.89 16.5985
#Mann= 3 , 0 , 0
  9882.7    0.08       0  9882.7    0.08       010500.89    0.08       0
#XS Ineff= 2 , 0
       0                10384.51       0
Bank Sta=9882.7,10500.89
Exp/Cntr=0.3,0.1

Type RM Length L Ch R = 1 ,222.0044,177.030000,177.030000,177.030000
XS GIS Cut Line= 6
 1215068.4611224605155.2004433431214853.13224224605203.402551707
1214763.14241265605208.7697476951214707.49488925605202.477928594
1214635.11714584605184.6670254731214451.05317787 605106.75287724
#Sta/Elev= 30
9859.194 16.16499883.58314.815859900.22416.284119913.70215.66778 9923.8514.42097
9930.61511.223389944.1452.1613369947.5280.7326039957.676  -0.9999967.823  -0.999
9971.206 0.172999981.3541.06464710011.810.95208610038.772.76057110085.561.317211
10141.591.08698110151.432.51195210177.7210.2488810190.9315.4389610207.4417.53816
10217.3417.9732610233.9917.5683110254.8918.2411210264.2319.1879810287.9917.78234
10315.59 18.700710332.9916.2652710350.3914.8044310389.1815.7282110500.8816.01432
#Mann= 3 , 0 , 0
9859.194    0.08       09859.194    0.08       010500.88    0.08       0
#XS Ineff= 2 , 0
       09880.901        10267.81       0
Bank Sta=9859.194,10500.88
Exp/Cntr=0.3,0.1

Type RM Length L Ch R = 1 , 44.9744,0.000000,0.000000,0.000000
XS GIS Cut Line= 5
1215419.07742923605368.3771873711215035.04018152605071.322735071
1214759.32113186604930.180840582 1214629.6675311604871.098187104
1214450.77838579604734.879847094
#Sta/Elev= 30
9391.42112.256939420.6869.4584839450.30312.537199629.81615.146099667.35212.15453
9699.169 14.59669763.87414.777989782.12412.043889815.30616.096439844.30912.01889
9899.57217.168399914.31510.226819933.9276.72143210006.460.47650310080.175.633118
10102.295.43565710168.6315.9762210201.4714.1641310233.9221.3893110262.7614.66081
10296.6213.4411610320.35 17.493910356.3114.34165 10382.717.88771 10405.813.73265
10458.5220.00082 10475.919.39543 10485.6 16.856910500.64 18.080710554.0113.79009
#Mann= 3 , 0 , 0
9391.421  0.0399       09391.421  0.0399       010554.01  0.0399       0
#XS Ineff= 2 , 0
       09874.384        10167.35       0
Bank Sta=9391.421,10554.01
Exp/Cntr=0.3,0.1